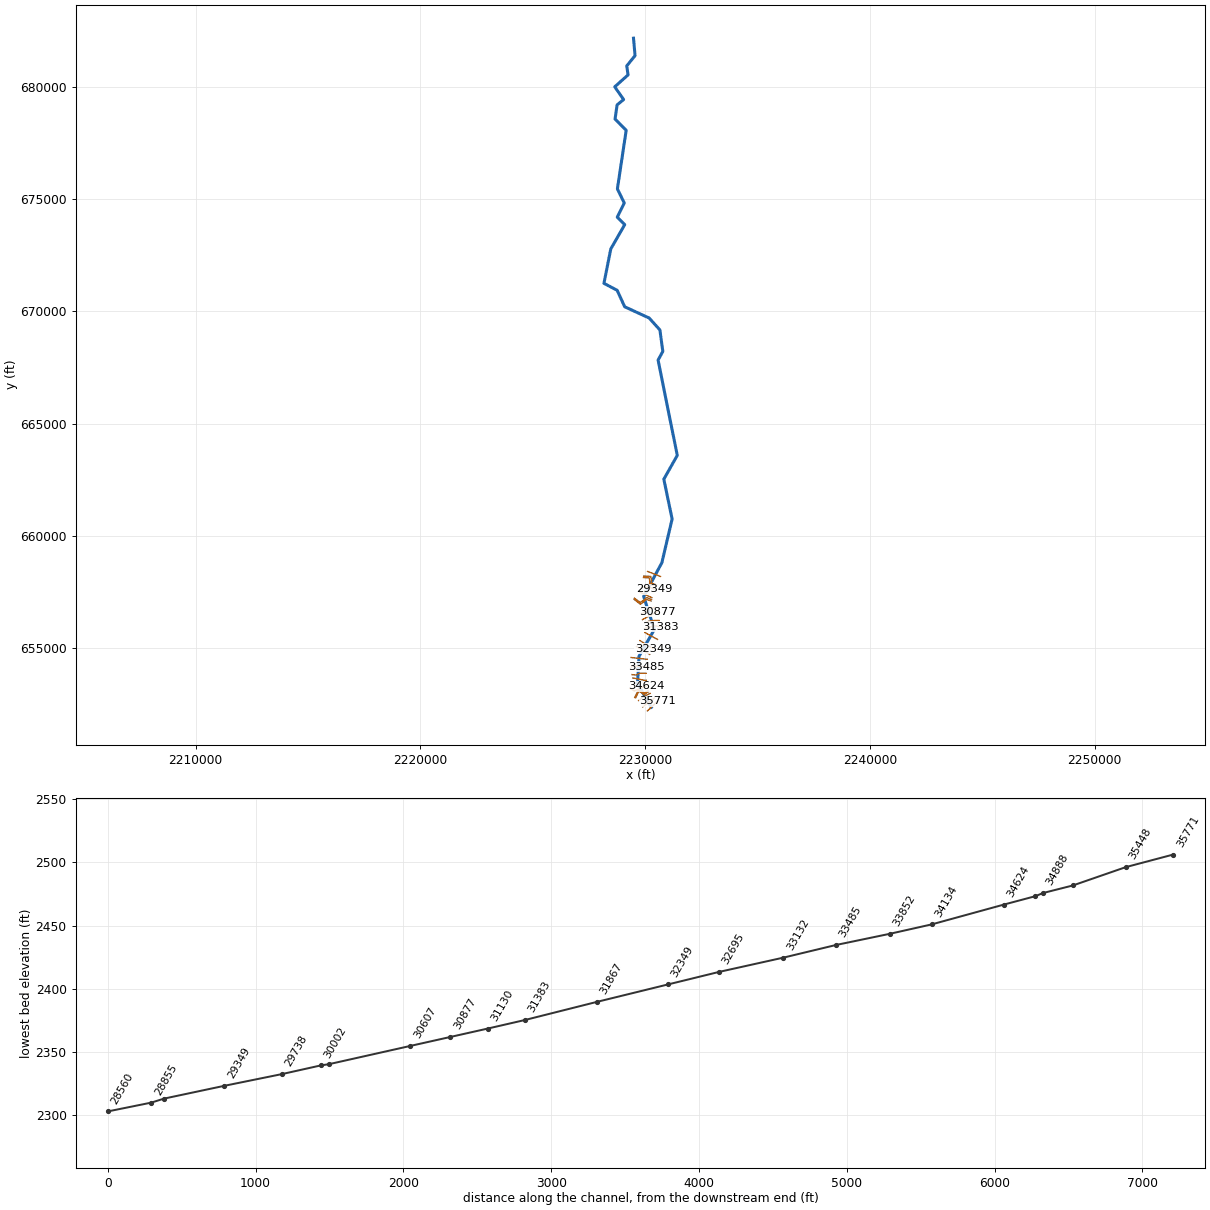
--- LONGRN.prj (project) ---

Proj Title=LONGRN
Current Plan=p01
Default Exp/Contr=0,0
English Units
Geom File=g01
Flow File=f01
Plan File=p01
BEGIN DESCRIPTION:
----------MODEL BY WSP USA 2022----------
AFH study
Randolph County, WV
HEC-RAS Version: RAS 6.2
Vertical Datum: NAVD88
Projection: NAD 1983 StatePlane West Virginia S FIPS 4702 (US Feet)
Terrain: 1-meter LIDAR (FEMA Region III 3DEP collected 2016-2018)
Land Use: 2019 NLCD
Hydrologic Method:
WV SIR2010-5033 regression equations
Additional Model Notes:
None
END DESCRIPTION:
DSS Export Rating Curves= 0
DSS Export Rating Curve Sorted= 0
DSS Export Volume Flow Curves= 0
DXF OffsetX= 0
DXF OffsetY= 0
DXF ScaleX= 0
DXF ScaleY= 0

--- LONGRN.p01 (plan) ---

Plan Title=Floodplain
Program Version=6.20
Short Identifier=Floodplain
Geom File=g01
Flow File=f01
Subcritical Flow
K Sum by GR= 0
Std Step Tol= 0.01
Critical Tol= 0.01
Num of Std Step Trials= 20
Max Error Tol= 0.3
Flow Tol Ratio= 0.001
Split Flow NTrial= 30
Split Flow Tol= 0.02
Split Flow Ratio= 0.02
Log Output Level= 0
Friction Slope Method= 1
Unsteady Friction Slope Method= 2
Unsteady Bridges Friction Slope Method= 1
Parabolic Critical Depth
Global Vel Dist= 0 , 0 , 0
Global Log Level= 0
CheckData=True
Encroach Param=-1 ,0,0, 0
Mapping Interval=1HOUR
Computation Time Step Use Courant=        0
Computation Time Step Use Time Series=    0
Computation Time Step Count To Double=0
Computation Time Step Max Doubling=0
Computation Time Step Max Halving=0
Computation Time Step Residence Courant=0
Run HTab= 0
Run UNet= 0
Run Sediment= 0
Run PostProcess= 0
Run WQNet= 0
Run RASMapper=-1
UNET Theta= 0
UNET Theta Warmup= 0
UNET ZTol= 0
UNET ZSATol= 0
UNET MxIter= 0
UNET Max Iter WO Improvement= 0
UNET MaxInSteps= 0
UNET DtIC= 0
UNET DtMin= 0
UNET MaxCRTS= 0
UNET WFStab= 0
UNET SFStab= 0
UNET WFX= 1
UNET SFX= 1
UNET Gravity=32.174
UNET 1D Methodology=Finite Difference
UNET DSS MLevel= 1
UNET Pardiso=0
UNET DZMax Abort= 0
UNET Use Existing IB Tables= 0
UNET Froude Reduction=False
UNET Froude Limit= 0
UNET Froude Power= 0
UNET D1 Cores= 0
UNET WindReference=Eulerian
UNET WindDragFormulation=Hsu (1988)
UNET D2 Coriolis=0
UNET D2 Cores= 0
UNET D2 Theta= 1
UNET D2 Theta Warmup= 1
UNET D2 Z Tol= 0.01
UNET D2 Volume Tol= 0.01
UNET D2 Max Iterations= 20
UNET D2 Equation= 0
UNET D2 RampUpFraction=0.1
UNET D2 TimeSlices= 1
UNET D2 Turbulence Formulation=Non-Conservative (original)
UNET D2 Eddy Viscosity=0.3
UNET D2 Transverse Eddy Viscosity=0.1
UNET D2 Smagorinsky Mixing=0
UNET D2 BCVolumeCheck=0
UNET D2 Cores=0
UNET D2 SolverType=PARDISO (Direct)
UNET D2 Minimum Iterations= 2147483647
UNET D2 Maximum Iterations= 2147483647
UNET D2 Restart Number= 10
UNET D2 Relaxation Coeff=1.3
UNET D2 SOR Precondition Iterations= 10
UNET D2 ILUT Maximum Fill= 8
UNET D2 ILUT Tolerance=1E-08
UNET D1D2 MaxIter= 0
UNET D1D2 ZTol=0.01
UNET D1D2 QTol=0.1
UNET D1D2 MinQTol=1
Write IC File= 0
Write IC File at Fixed DateTime=0
Write IC File at Sim End=0
Echo Input=False
Echo Parameters=False
Echo Output=False
Write Detailed= 0
HDF Write Warmup=0
HDF Write Time Slices=0
HDF Flush=0
HDF Compression= 1
HDF Chunk Size= 1
HDF Spatial Parts= 1
HDF Use Max Rows=0
HDF Fixed Rows= 1
Calibration Method= 0
Calibration Iterations= 20
Calibration Max Change=0.05
Calibration Tolerance=0.2
Calibration Maximum=1.5
Calibration Minimum=0.5
Calibration Optimization Method= 1
WQ AD Non Conservative
WQ ULTIMATE=-1
WQ Max Comp Step=1HOUR
WQ Output Interval=15MIN
WQ Output Selected Increments= 0
WQ Output face flow=0
WQ Output face velocity=0
WQ Output face area=0
WQ Output face dispersion=0
WQ Output cell volume=0
WQ Output cell surface area=0
WQ Output cell continuity=0
WQ Output cumulative cell continuity=0
WQ Output face conc=0
WQ Output face dconc_dx=0
WQ Output face courant=0
WQ Output face peclet=0
WQ Output face adv mass=0
WQ Output face disp mass=0
WQ Output cell mass=0
WQ Output cell source sink temp=0
WQ Output nsm pathways=0
WQ Output nsm derived pathways=0
WQ Create Restart=0
WQ Fixed Restart=0
WQ System Summary=0
WQ Write To DSS=0
Sorting and Armoring Iterations= 10
XS Update Threshold= 0.02
Bed Roughness Predictor= 0
Hydraulics Update Threshold= 0.02
Energy Slope Method= 1
Volume Change Method= 1
Sediment Retention Method= 0
Sediment TS Multiplier= 1
Warm Up Method= 0
XS Weighting Method= 0
Number of US Weighted Cross Sections= 1
Number of DS Weighted Cross Sections= 1
Upstream XS Weight=0
Main XS Weight=1
Downstream XS Weight=0
Number of DS XS's Weighted with US Boundary= 1
Upstream Boundary Weight= 1
Weight of XSs Associated with US Boundary= 0
Number of US XS's Weighted with DS Boundary= 1
Downstream Boundary Weight= 0.5
Weight of XSs Associated with DS Boundary= 0.5
Percentile Method= 0
Sediment Output Level= 3
Mass or Volume Output= 0
Output Increment Type= 1
Profile and TS Output Increment= 1
Transport Output Increment 1
XS Output Flag= 0
XS Output Increment= 10
Read HDF5 Sediment Hotstart= 0
Sediment Hotstart Type= 0
Write Gradation File= 0
Read Gradation Hotstart= 0
Write HDF5 File= 1
Write Binary Output= 1
Write DSS Sediment File= 0
DSS Sediment Output Type= 1
SV Curve= 0
Specific Gage Flag= 0
Subcell Erosion Methods= 0
Subcell Deposition Methods= 0
Advection Scheme= 1
Matrix Solver= 0
Implicit Weighting Factor= 1
Maximum Outer Loop Convergence Iterations= 5
Convergence Maximum Absolute= 0.001
Convergence RMSE= 0.0001
Grain Fractions Max Abs Error= 0.001
Max Subgrid Regions= 1
Max Subgrid Length Scale= 3.402823E+38
Initial Layer Thickness= 3.402823E+38
Min Layer Thickness= 3.402823E+38
Max Layer Thickness= 3.402823E+38
Number of Layers= 5

--- LONGRN.f01 (steady flow) ---

Flow Title=Flow
Program Version=6.20
Number of Profiles= 1
Profile Names=P100yr
River Rch & RM=LONGRN,Main,35771
     454
River Rch & RM=LONGRN,Main,33132
     514
River Rch & RM=LONGRN,Main,30056
     599
River Rch & RM=LONGRN,Main,28939
     678
River Rch & RM=LONGRN,Main,26323
     754
River Rch & RM=LONGRN,Main,22622
     839
River Rch & RM=LONGRN,Main,19593
     947
River Rch & RM=LONGRN,Main,16134
    1060
River Rch & RM=LONGRN,Main,13684
    1330
River Rch & RM=LONGRN,Main,10863
    1510
River Rch & RM=LONGRN,Main,5566
    1680
Boundary for River Rch & Prof#=LONGRN,Main            , 1
Up Type= 0
Dn Type= 3
Dn Slope=0.00736
DSS Import GetInterval= 0
DSS Import GetPeak= 0
DSS Import FillOption= 0

--- LONGRN.g01 (geometry) ---

Geom Title=Geometry
Program Version=6.20

River Reach=LONGRN          ,Main
Reach XY= 30
2230276.91194851652364.166291461     2229663.481      653420.141
     2229731.259      654637.812     2230414.574      655831.078
     2229938.429      657298.119     2230748.018      658804.735
      2231204.02      660747.025     2230834.365       662522.89
     2231434.021      663579.679     2230579.548      667823.902
     2230790.402      668213.253     2230660.056      669166.631
     2230182.111      669697.561     2229093.541      670198.082
     2228757.994      670931.872      2228168.95       671241.47
 2228475.3448689672776.509914252     2229095.582      673854.697
     2228762.374      674186.803     2229073.932      674819.504
     2228768.656      675446.2282229159.11701571678053.741116449
     2228664.574      678556.864     2228755.904       679188.35
     2229046.174      679423.082     2228651.016      679991.136
     2229242.287      680521.255     2229185.279      680921.889
     2229554.157      681379.393     2229485.971      682154.846

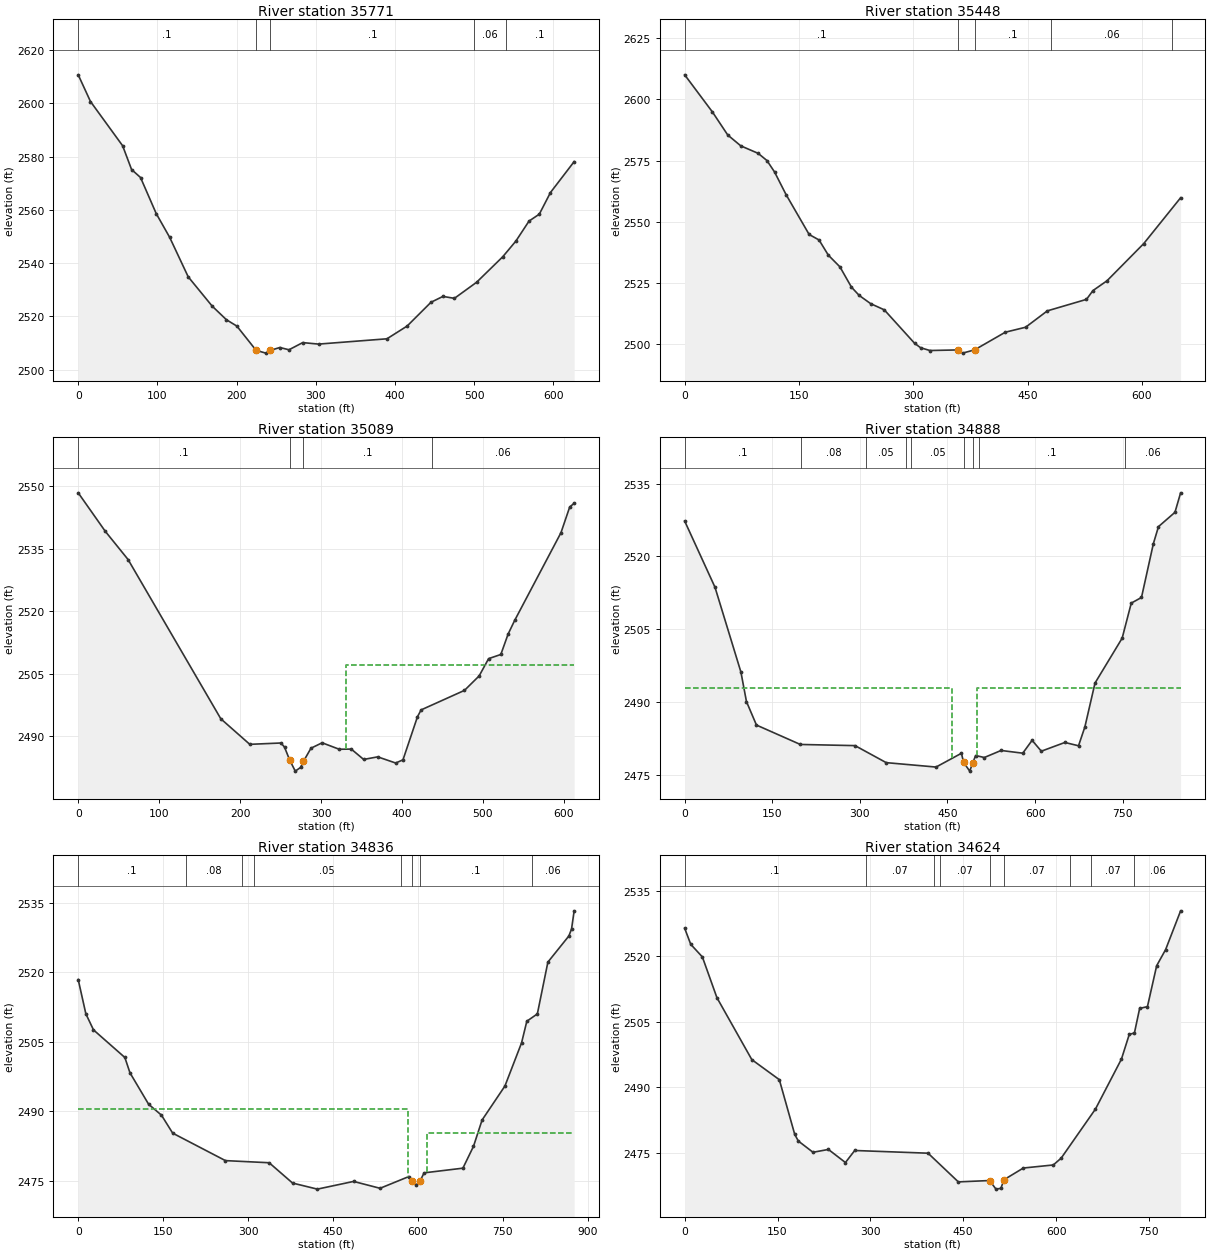
Type RM Length L Ch R = 1 ,35771   ,324.4,322.3,318.3
XS GIS Cut Line= 2
2230104.97807099652205.0858316712230557.37612975652638.245313194
#Sta/Elev= 30
       0 2610.67    15.5 2600.65    56.1 2584.04    67.4 2575.11    78.7 2572.12
    98.5 2558.59   115.5 2549.66   138.9 2534.84   169.2 2523.83   187.2 2518.72
   200.4 2516.33  224.71 2507.22     237 2506.19   242.8 2507.24   254.6  2508.3
   266.2 2507.45   283.5 2510.14   303.5 2509.58   389.9 2511.57   415.4 2516.36
   445.5 2525.28   460.6 2527.48   475.1 2526.76   503.1 2532.79   536.1 2542.36
   552.7 2548.25   569.3 2555.76   582.3 2558.36   596.4 2566.49   626.3 2578.09
#Mann= 5, -1 ,  0
       0     0.1       0  224.71   0.045       0   242.8     0.1       0
     500    0.06       0     540     0.1       0
Bank Sta=224.71,242.8
XS Rating Curve= 0 ,0
Exp/Cntr(USF)=0,0
Exp/Cntr=0.3,0.1

Type RM Length L Ch R = 1 ,35448   ,358.2,358.9,357.9
XS GIS Cut Line= 2
2229894.72301335652379.3888598142230410.57213574652776.085113484
#Sta/Elev= 30
       0 2610.09    36.5 2594.85    56.5 2585.47    73.6 2581.03    96.4 2577.96
   107.9 2575.03   117.9 2570.35     133 2561.09   163.3 2544.76   176.3 2542.51
   188.5 2536.29   203.7 2531.51   218.8 2523.22   228.9 2519.84     244 2516.46
   261.9 2513.92   301.8 2500.19   309.6 2498.41   321.8 2497.28   358.9 2497.52
   364.6 2496.21   380.3 2497.53   420.7 2504.77   447.3  2506.8   475.8  2513.5
   527.2 2518.21   535.7 2521.81   554.1 2525.81   602.3 2541.03   650.7 2559.79
#Mann= 5, -1 ,  0
       0     0.1       0   358.9   0.045       0   380.3     0.1       0
     480    0.06       0     640     0.1       0
Bank Sta=358.9,380.3
XS Rating Curve= 0 ,0
Exp/Cntr=0.3,0.1

Type RM Length L Ch R = 1 ,35089   ,211.8,201.1,191.9
BEGIN DESCRIPTION:
Structure XS 4
END DESCRIPTION:
XS GIS Cut Line= 3
2229710.97480515652663.5888370582229956.18460627652848.712934384
2230229.06716808652986.251467797
#Sta/Elev= 30
       0 2548.36    33.4 2539.15    61.6 2532.38   176.2 2494.22     212  2488.1
   250.5 2488.42   254.9 2487.44   261.32484.328   268.2 2481.68   274.8 2482.57
   278.32484.008   287.6 2487.17   301.4 2488.47   322.5 2486.92   337.4 2486.96
   352.7 2484.48   370.1  2485.1   392.3 2483.62   401.3 2484.39   419.2 2494.71
   423.7 2496.35   477.3 2501.03   495.4 2504.49   507.1 2508.63   522.2 2509.63
   531.2 2514.52   539.3 2517.79   596.5  2538.8   607.3 2544.96   612.8 2545.86
#Mann= 4, -1 ,  0
       0     0.1       0   261.3   0.045       0   278.3     0.1       0
  437.24    0.06       0
#XS Ineff= 2 , 0
                          330.48         2507.13
Permanent Ineff=
       F       F
Bank Sta=261.3,278.3
XS Rating Curve= 0 ,0
Exp/Cntr(USF)=0,0
Exp/Cntr=0.3,0.1

Type RM Length L Ch R = 1 ,34888   ,52.4,51.8,53.6
BEGIN DESCRIPTION:
Structure XS 3 Disconnected without IFA
END DESCRIPTION:
XS GIS Cut Line= 6
2229582.21623402652790.4540809232229724.80413741653086.258025223
2229873.06018583652992.0953998732229910.45810796652963.379138241
2229938.50654955652929.9881363442230156.50809071653060.949056054
#Sta/Elev= 30
       0  2527.3    51.9 2513.65    96.3 2496.16   105.8 2490.07   122.9 2485.23
     198 2481.23   291.7 2480.99   345.1 2477.48   430.4 2476.57   473.9 2479.41
  477.592477.529   488.1 2475.73   493.4 2477.48   498.2 2478.95   513.1 2478.54
   541.8 2479.99   578.9 2479.43   594.9 2482.08   610.7 2479.84     651 2481.64
   674.4 2480.96   685.3 2484.86   702.6 2493.89   749.1 2503.15   764.7 2510.38
   782.2 2511.54   802.5 2522.62   811.3 2526.15   839.5  2529.1   849.2 2533.12
#Mann= 9, -1 ,  0
       0     0.1       0     200    0.08       0     310    0.05       0
  378.38    0.08       0  388.38    0.05       0  477.59   0.045       0
   493.4    0.05       0  504.16     0.1       0  753.36    0.06       0
#XS Ineff= 2 , 0
          458.48 2492.81  500.36         2492.93
Permanent Ineff=
       F       F
Bank Sta=477.59,493.4
XS Rating Curve= 0 ,0
Exp/Cntr(USF)=0,0
Exp/Cntr=0.3,0.1

Type RM Length L Ch R = 1 ,34836   ,212,212.4,221.5
BEGIN DESCRIPTION:
Structure XS 2 Disconnected without IFA
END DESCRIPTION:
XS GIS Cut Line= 6
2229540.50249491652802.788585371 2229704.4606395 653144.00429225
2229774.58174349653109.9454703152229913.48831138653029.807065762
2229950.21841347652998.4195239792230132.15767258653104.671102284
#Sta/Elev= 30
       0 2518.42    13.5 2511.04      27 2507.57    82.4 2501.62    91.4 2498.32
   124.4 2491.53     147 2489.19   166.9  2485.3     260 2479.38   337.3 2478.92
   378.6 2474.54   422.4 2473.23   486.4 2474.89   533.2 2473.41   583.8 2475.93
   589.8 2475.07   597.4  2474.1  604.082475.039   610.9 2476.74   679.5 2477.75
   698.2 2482.46   713.4 2488.14   753.7 2495.46   783.1 2504.77   792.4 2509.44
     811 2511.02   829.6 2522.19   866.7 2527.83   871.4 2529.33     876 2533.25
#Mann= 8, -1 ,  0
       0     0.1       0     190    0.08       0     290    0.07       0
     310    0.05       0   569.6     0.1       0   589.8   0.045       0
  604.08     0.1       0  800.99    0.06       0
#XS Ineff= 2 , 0
          583.39 2490.52  616.27         2485.43
Permanent Ineff=
       F       F
Bank Sta=589.8,604.08
XS Rating Curve= 0 ,0
Exp/Cntr(USF)=0,0
Exp/Cntr=0.3,0.1

Type RM Length L Ch R = 1 ,34624   ,493.3,489.8,474.7
BEGIN DESCRIPTION:
Structure XS 1
END DESCRIPTION:
XS GIS Cut Line= 4
2229323.85385195653213.5721125222229521.34465391653091.527234907
2229880.82229343653253.5140724692230047.24712654653306.770019064
#Sta/Elev= 30
       0 2526.43     9.8 2522.75    28.6 2519.85    52.1 2510.51   108.5  2496.3
   152.9 2491.71   177.8 2479.16   183.6 2477.64   207.3 2475.06   232.2 2475.71
   259.7 2472.71   274.7 2475.47   393.2 2474.85   442.1 2468.27   492.6 2468.58
   502.9 2466.61   510.8 2466.79  515.942468.772   547.1 2471.45   595.5 2472.15
   608.2 2473.71   663.6 2484.97   705.6 2496.43   718.2 2502.07   726.6 2502.44
     735 2508.05   747.6 2508.46   762.5 2517.84     777 2521.55   801.2 2530.43
#Mann= 9, -1 ,  0
       0     0.1       0  292.16    0.07       0  402.16    0.05       0
  412.16    0.07       0   492.6   0.045       0  515.94    0.07       0
  622.16     0.1       0  656.45    0.07       0  726.45    0.06       0
Bank Sta=492.6,515.94
XS Rating Curve= 0 ,0
Exp/Cntr(USF)=0,0
Exp/Cntr=0.3,0.1

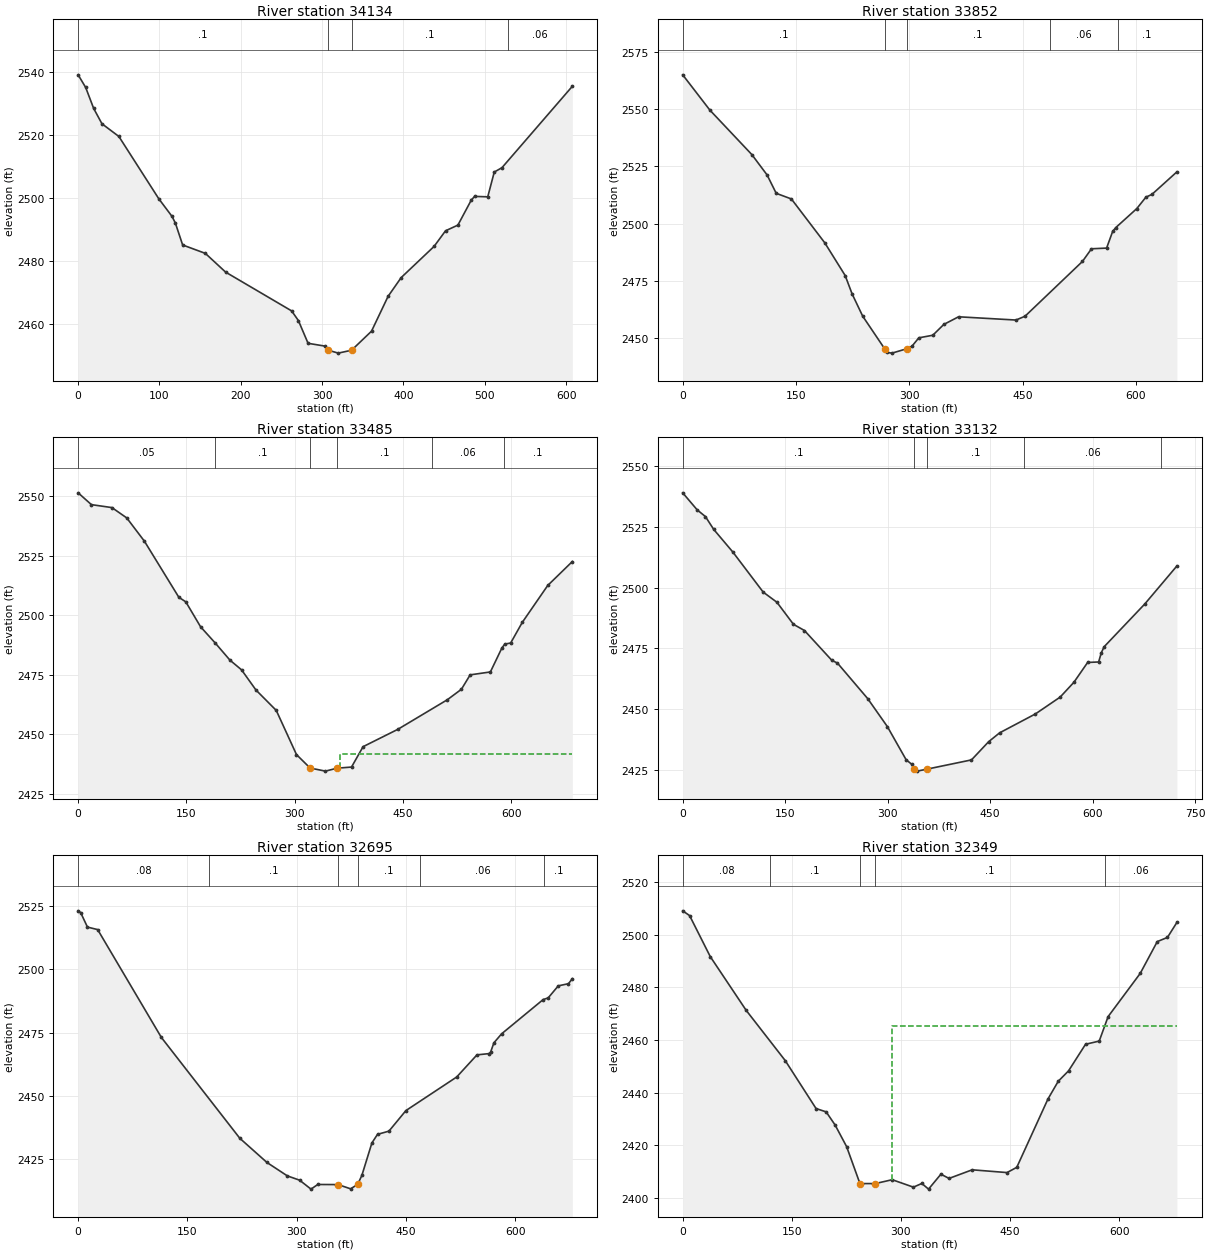
Type RM Length L Ch R = 1 ,34134   ,276.1,281.7,295.4
XS GIS Cut Line= 3
 2229455.1143789653674.7375818952229943.29388936653572.663684253
2230052.02478033653568.225688704
#Sta/Elev= 30
       0 2539.03     9.3 2535.02    19.1 2528.39    29.3 2523.53    50.1 2519.51
    99.2 2499.77   115.5 2494.18   119.6 2492.05   128.5 2485.15   156.4 2482.49
   181.3 2476.56   262.5 2464.27   270.8 2461.21   282.7 2454.01   303.5 2453.12
   307.6 2451.82   319.8  2450.9   336.2 2451.82   360.7 2457.85   381.1  2468.9
   397.2 2474.83   437.6 2484.69   451.7 2489.64   466.9 2491.44   483.3 2499.34
   487.4 2500.53   503.6  2500.4   511.6 2508.24   521.1 2509.63   607.6  2535.4
#Mann= 4, -1 ,  0
       0     0.1       0   307.6   0.045       0   336.2     0.1       0
  528.74    0.06       0
Bank Sta=307.6,336.2
XS Rating Curve= 0 ,0
Exp/Cntr(USF)=0,0
Exp/Cntr=0.3,0.1

Type RM Length L Ch R = 1 ,33852   ,371.8,367.7,355.2
XS GIS Cut Line= 4
2229417.05175849653821.577502823 2229610.1045649 653801.60652285
2229740.71331457 653878.601308222230049.34424667653879.025383981
#Sta/Elev= 30
       0 2564.88      36 2549.48    91.6 2530.07   111.7 2521.22   123.8  2513.2
   143.9 2510.74   188.1 2491.61   215.1 2477.34   224.3 2469.31   238.3 2459.62
   267.42445.382   270.8  2443.8   277.1  2443.5   296.62445.405   303.3 2446.43
   312.6 2450.17   331.1  2451.3   345.7 2456.02   365.2 2459.35   441.2 2457.93
   453.2 2459.59   529.2 2483.48   541.2 2489.01   561.2 2489.31   569.2 2496.56
   573.2 2498.21   601.2 2506.55   613.2 2511.51   621.2 2512.73   654.3 2522.57
#Mann= 5, -1 ,  0
       0     0.1       0   267.4   0.045       0   296.6     0.1       0
   485.7    0.06       0   575.7     0.1       0
Bank Sta=267.4,296.6
XS Rating Curve= 0 ,0
Exp/Cntr(USF)=0,0
Exp/Cntr=0.3,0.1

Type RM Length L Ch R = 1 ,33485   ,352,353.1,352.9
XS GIS Cut Line= 3
2229390.42378519654161.0841623712229585.69558938654203.245120093
2230069.43710429 654174.39814902
#Sta/Elev= 30
       0 2551.46    18.4  2546.5    46.8 2545.26    67.3 2540.93    91.8 2531.14
   139.5 2507.57   149.1 2505.67   169.6 2495.18     190 2488.33   210.3 2481.16
   226.3 2477.11   246.3 2468.62   274.4 2460.05   302.4  2441.5   321.3 2435.85
   342.5 2434.56   358.5 2435.79   378.6 2436.27   394.6 2444.83   442.7 2452.11
   511.3 2464.55   530.8 2468.95   542.9    2475   570.9 2476.22   586.9 2486.33
   590.9 2487.92     599 2488.38     615 2497.01   650.3 2512.54   684.4  2522.6
#Mann= 6, -1 ,  0
       0    0.05       0     190     0.1       0   321.3   0.045       0
   358.5     0.1       0  489.77    0.06       0  589.77     0.1       0
#XS Ineff= 2 , 0
                          362.64         2441.56
Permanent Ineff=
       F       F
Bank Sta=321.3,358.5
XS Rating Curve= 0 ,0
Exp/Cntr(USF)=0,0
Exp/Cntr=0.3,0.1

Type RM Length L Ch R = 1 ,33132   ,437.6,437,430.4
XS GIS Cut Line= 2
2229379.07800207654582.8278720152230098.03328112654502.943952121
#Sta/Elev= 30
       0 2538.91    21.2 2531.91    33.3 2529.15    45.4 2523.89    73.5 2514.56
   117.8 2498.15   137.9 2493.98   162.1 2484.92   178.2 2482.38   218.4  2470.1
   226.5 2469.01   270.8 2454.41   299.5 2442.95   327.1 2429.29   335.1 2427.49
   338.5 2425.41   343.2 2424.64   357.1 2425.43   422.7 2429.25   447.8 2436.72
   463.9 2440.36   516.3 2448.13   552.5 2455.04   572.6 2461.11   592.7 2469.26
   608.8 2469.46   612.8  2473.3   616.9 2475.72   676.2 2493.22   723.4 2508.89
#Mann= 5, -1 ,  0
       0     0.1       0   338.5   0.045       0   357.1     0.1       0
     500    0.06       0     700     0.1       0
Bank Sta=338.5,357.1
XS Rating Curve= 0 ,0
Exp/Cntr(USF)=0,0
Exp/Cntr=0.3,0.1

Type RM Length L Ch R = 1 ,32695   ,342.2,345.6,345.2
XS GIS Cut Line= 2
2229621.19955378655070.8732500482230204.79596855654724.709597176
#Sta/Elev= 30
       0 2522.96     3.5 2522.25    12.8 2516.55    26.8 2515.57   114.3 2473.06
     222 2433.33   259.2 2423.81   287.2 2418.52   304.1 2416.82   319.7  2413.3
     329 2415.13   356.9 2415.09   374.1 2413.42  383.782415.176   389.5 2418.67
   403.3 2431.49     411 2434.88   426.7 2436.15     450 2444.25   519.7 2457.48
   547.6 2466.21   563.9 2466.69   566.2 2467.22   570.8 2470.95   581.4  2474.5
   638.4 2487.99   645.3 2488.65   659.2  2493.4   673.2 2494.25   678.5 2496.24
#Mann= 6, -1 ,  0
       0    0.08       0     180     0.1       0   356.9   0.045       0
  383.78     0.1       0     470    0.06       0     640     0.1       0
Bank Sta=356.9,383.78
XS Rating Curve= 0 ,0
Exp/Cntr(USF)=0,0
Exp/Cntr=0.3,0.1

Type RM Length L Ch R = 1 ,32349   ,479.5,482.1,481.5
XS GIS Cut Line= 2
2229772.09140246655337.1529830272230351.24982169654982.113339055
#Sta/Elev= 30
       0 2509.13     9.5 2507.31    37.9 2491.73    87.3  2471.3   140.9 2452.24
   183.3 2434.01   197.2 2432.74   209.5 2427.74   225.3 2419.54  243.62  2405.5
   264.7  2405.5     288 2406.97   317.1 2404.14   328.7 2405.54   337.9 2403.39
   354.9 2409.06   366.1 2407.46   397.9 2410.73   445.8 2409.68   459.2 2411.68
   502.1 2437.67   516.2 2444.38   530.3 2448.31   553.7 2458.43   572.5 2459.64
   584.7 2468.93   628.8 2485.33   652.3 2497.44   666.3 2499.03   679.3 2504.74
#Mann= 5, -1 ,  0
       0    0.08       0     120     0.1       0  243.62   0.045       0
   264.7     0.1       0     580    0.06       0
#XS Ineff= 2 , 0
                          287.58         2465.38
Permanent Ineff=
       F       F
Bank Sta=243.62,264.7
XS Rating Curve= 0 ,0
Exp/Cntr(USF)=0,0
Exp/Cntr=0.3,0.1

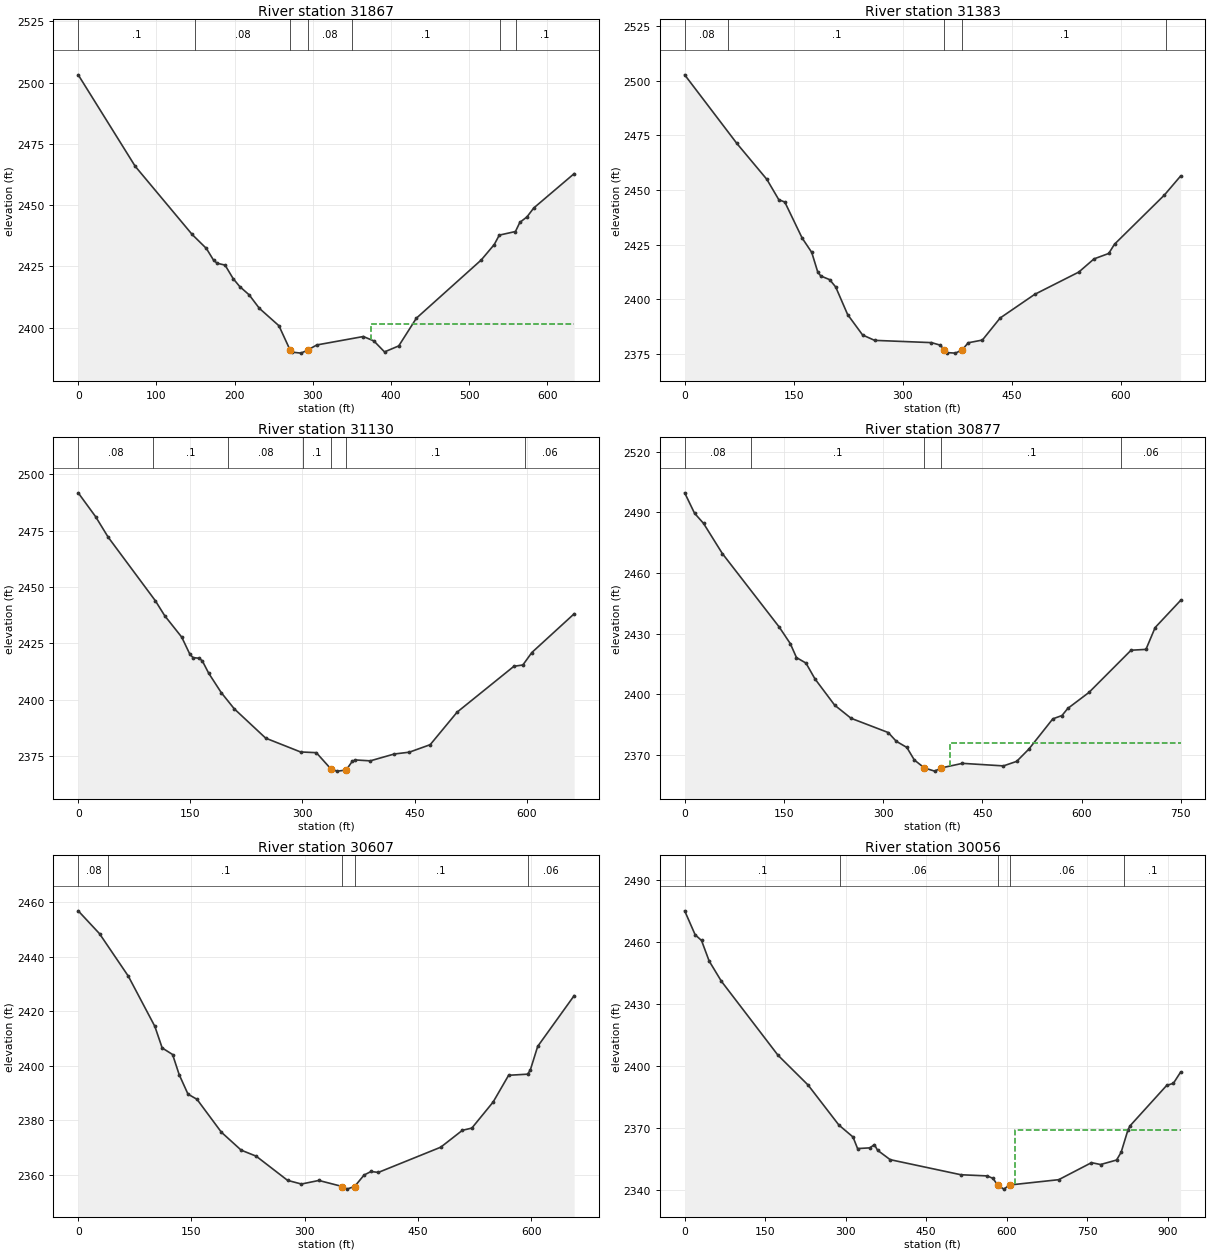
Type RM Length L Ch R = 1 ,31867   ,474.9,484.4,492.7
XS GIS Cut Line= 2
2229996.21017772655692.192626998 2230553.1786192655388.189931848
#Sta/Elev= 30
       0  2503.2    72.9 2465.86   145.8    2438     164 2432.29   173.1 2427.55
   177.7 2426.27   187.9  2425.5   198.3 2419.95   206.7 2416.73   218.7 2413.36
   231.7 2407.87   256.8 2400.74  270.992390.885   273.5 2389.96   285.2 2389.56
     294 2390.91   305.3  2392.9   364.8 2396.34   378.2 2394.55   391.9 2390.06
   410.1 2392.51   432.6 2403.81   515.6 2427.59   532.3 2433.91   538.7 2437.74
   559.4 2439.22     565 2442.94   574.1 2445.18   582.9 2448.85   634.5 2462.85
#Mann= 7, -1 ,  0
       0     0.1       0     150    0.08       0  270.99   0.045       0
     294    0.08       0     350     0.1       0     540    0.06       0
     560     0.1       0
#XS Ineff= 2 , 0
                          374.76         2401.49
Permanent Ineff=
       F       F
Bank Sta=270.99,294
XS Rating Curve= 0 ,0
Exp/Cntr(USF)=0,0
Exp/Cntr=0.3,0.1

Type RM Length L Ch R = 1 ,31383   ,253.8,252.6,250.9
XS GIS Cut Line= 3
2230018.40015547655891.9024267322230428.91474381655991.757326599
2230686.31848569655958.472359977
#Sta/Elev= 30
       0 2502.76    71.8 2471.32     113 2454.89   129.4 2445.58   137.7 2444.49
   161.5 2428.03   174.7 2421.45     183 2412.44   187.1 2410.65   199.4 2408.95
   207.7 2405.58   224.1 2392.96   244.7  2383.6   261.2 2381.15   339.4 2380.11
   351.7 2378.93  357.032376.731   360.1 2375.56   372.3  2375.3   381.5 2376.76
   389.9 2380.04   409.4 2381.29   433.8 2391.38   481.3 2402.21     542 2412.43
   562.9 2418.46   583.1 2420.94   591.1 2425.19   659.7 2447.71     682 2456.42
#Mann= 5, -1 ,  0
       0    0.08       0      60     0.1       0  357.03   0.045       0
   381.5     0.1       0  662.48    0.06       0
Bank Sta=357.03,381.5
XS Rating Curve= 0 ,0
Exp/Cntr(USF)=0,0
Exp/Cntr=0.3,0.1

Type RM Length L Ch R = 1 ,31130   ,248.5,252.8,256.7
XS GIS Cut Line= 4
2229982.01547414656136.9802102752230220.78052232656214.142085598
2230407.13373064656230.1568144392230632.79581885656230.156814439
#Sta/Elev= 30
       0 2491.69    23.3 2481.13    40.1 2472.06   103.2 2443.93   115.8 2437.27
   138.5 2427.82   149.4 2420.25   153.6 2418.76     162 2418.47   166.2 2417.23
   174.6 2411.84   191.4 2403.26   208.8 2396.09   250.9  2383.1   297.5    2377
   318.6 2376.68   338.72369.272   346.7 2368.51   358.42368.944   366.7 2372.84
   370.8 2373.46   390.8 2373.06   422.9 2376.09     443 2376.89     471 2380.22
     507 2394.62     583 2414.91     595  2415.5     607 2421.01   663.6 2438.14
#Mann= 7, -1 ,  0
       0    0.08       0     100     0.1       0     200    0.08       0
  300.92     0.1       0   338.7   0.045       0   358.4     0.1       0
  597.96    0.06       0
Bank Sta=338.7,358.4
XS Rating Curve= 0 ,0
Exp/Cntr(USF)=0,0
Exp/Cntr=0.3,0.1

Type RM Length L Ch R = 1 ,30877   ,271.5,270.4,268.4
XS GIS Cut Line= 2
 2229883.0412912656269.1320484522230542.08363033656626.390690198
#Sta/Elev= 30
       0 2499.65    14.9 2489.55    28.6 2484.48    56.9 2469.61   142.8 2433.25
   159.6 2425.02     169 2418.08   183.3 2415.37   196.9 2407.55   226.7 2394.53
   251.5 2388.03   307.7 2380.97   319.8 2376.65   335.8  2373.6   347.1 2367.39
  362.442363.421   377.8 2361.87     388 2363.47   419.9 2365.72   481.8 2364.46
   501.8  2366.7   520.2 2372.77   556.4 2387.74   570.3  2389.4   579.1 2392.93
     611 2400.81   674.7 2421.73   697.2 2422.14   711.1 2432.96   749.6 2446.41
#Mann= 5, -1 ,  0
       0    0.08       0     100     0.1       0  362.44   0.045       0
     388     0.1       0     660    0.06       0
#XS Ineff= 2 , 0
                          400.52          2375.6
Permanent Ineff=
       F       F
Bank Sta=362.44,388
XS Rating Curve= 0 ,0
Exp/Cntr(USF)=0,0
Exp/Cntr=0.3,0.1

Type RM Length L Ch R = 1 ,30607   ,543,550.5,548.6
BEGIN DESCRIPTION:
Structure XS 4
END DESCRIPTION:
XS GIS Cut Line= 3
2229843.70645234656527.1572402122230290.66297544656783.392901663
2230428.97199724656813.966474904
#Sta/Elev= 30
       0 2456.88    28.2  2448.5    66.3 2432.94   101.5 2414.49   111.2 2406.58
     125 2404.17   133.7  2396.8   145.4 2389.63   157.3 2387.74   189.6 2375.67
   215.8 2369.09   235.7 2366.88   277.3    2358   295.6 2356.66   318.7 2357.97
   349.9 2355.74   355.6 2354.79     366 2355.75   378.6 2359.96   387.8 2361.26
   397.5 2360.92   480.1 2370.17   508.8 2376.37   521.3 2377.18   549.5 2386.74
     570 2396.55   595.1 2396.96   598.7 2398.45   608.5 2407.15   656.8 2425.77
#Mann= 5, -1 ,  0
       0    0.08       0      40     0.1       0   349.9   0.045       0
     366     0.1       0   595.2    0.06       0
Bank Sta=349.9,366
XS Rating Curve= 0 ,0
Exp/Cntr(USF)=0,0
Exp/Cntr=0.3,0.1

Type RM Length L Ch R = 1 ,30056   ,55,54.6,54.2
BEGIN DESCRIPTION:
Structure XS 3
END DESCRIPTION:
XS GIS Cut Line= 6
2229508.75325674657173.7557311352229793.19231157656954.058401477
2229890.83556919657025.1681651832229956.12070031657085.731820261
2230065.44686758657172.078602052 2230268.7796118657100.355065564
#Sta/Elev= 30
       0 2475.07    19.5 2463.49    31.4 2460.71    45.6 2450.78    68.4 2440.99
   173.9 2405.17     230 2390.74   287.4 2371.37   313.7 2365.59   322.2 2359.99
     345 2360.34   353.6 2361.91   359.4 2359.19   382.9 2354.63   514.8 2347.32
   563.9 2346.76   574.6 2345.54   583.1 2342.36   594.8 2340.36  605.332342.351
     697 2344.93   758.1 2353.17   775.1 2352.27   804.8 2354.44   813.3 2358.16
   826.2 2369.13   830.2 2371.07   898.1 2390.53   910.8 2391.61   924.2 2397.01
#Mann= 5, -1 ,  0
       0     0.1       0     290    0.06       0   583.1   0.045       0
  605.33    0.06       0  818.56     0.1       0
#XS Ineff= 2 , 0
                          615.16         2369.21
Permanent Ineff=
       F       F
Bank Sta=583.1,605.33
XS Rating Curve= 0 ,0
Exp/Cntr(USF)=0,0
Exp/Cntr=0.3,0.1

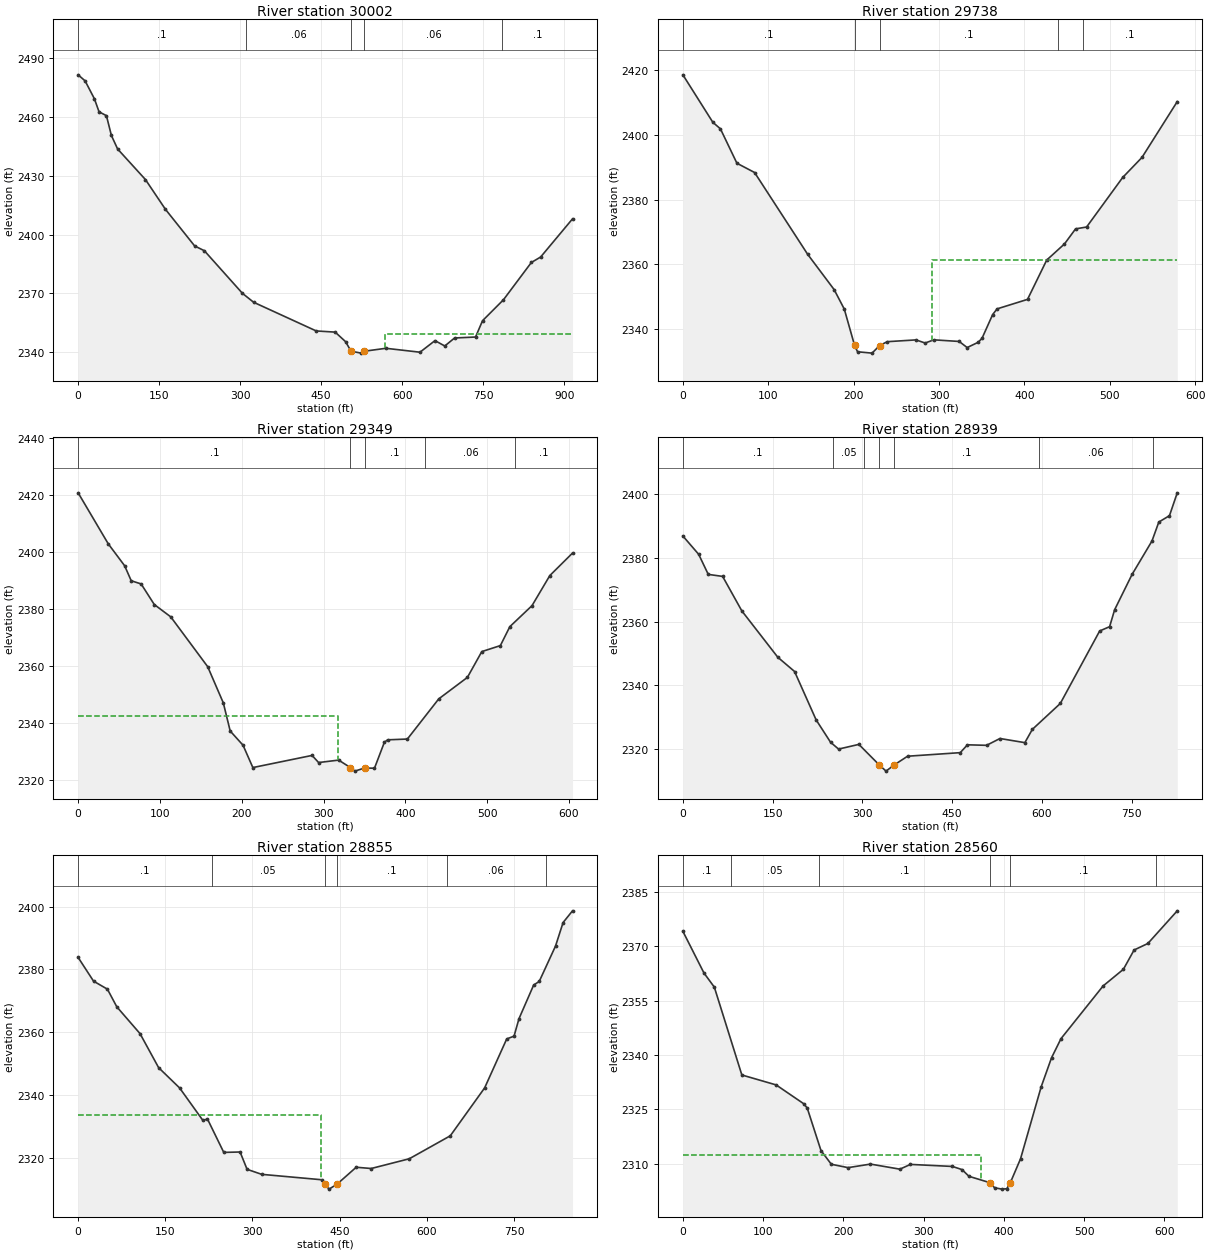
Type RM Length L Ch R = 1 ,30002   ,274.4,264,246.6
BEGIN DESCRIPTION:
Structure XS 2 Disconnected without IFA
END DESCRIPTION:
XS GIS Cut Line= 6
2229524.67335309657223.6386997052229788.94695254657034.720222994
2229982.11078828657171.6330516222230030.93241709657221.516020192
2230077.63136639657249.1108538692230290.96065751657164.203673324
#Sta/Elev= 30
       0 2481.64    12.9 2478.55    30.1 2469.41    38.7 2462.75    52.4 2460.75
    61.6 2450.63    73.1 2443.73   124.7 2428.08   161.6 2412.91   215.7 2394.18
   233.7 2391.73   304.2 2369.95   324.9 2365.39   440.8 2350.73   475.9 2350.13
   495.1 2345.26   505.3 2340.37     524 2339.39   530.1 2340.37   569.8 2341.86
   632.9 2339.86   660.7 2345.78   678.8 2343.04     697 2347.13   735.8 2347.62
   748.7 2355.95   787.4 2366.65   839.1 2385.72   856.3 2388.52   915.3 2408.02
#Mann= 5, -1 ,  0
       0     0.1       0     310    0.06       0   505.3   0.045       0
   530.1    0.06       0  785.66     0.1       0
#XS Ineff= 2 , 0
                          568.84         2349.05
Permanent Ineff=
       F       F
Bank Sta=505.3,530.1
XS Rating Curve= 0 ,0
Exp/Cntr(USF)=0,0
Exp/Cntr=0.3,0.1

Type RM Length L Ch R = 1 ,29738   ,388.2,389,390.6
BEGIN DESCRIPTION:
Structure XS 1
END DESCRIPTION:
XS GIS Cut Line= 3
2229776.52939801657494.0188201542230144.88302863657316.498998168
2230302.43187065657252.148062698
#Sta/Elev= 30
       0 2418.58    35.1  2403.9      44 2401.87    63.3 2391.24      84 2388.37
   146.1  2363.1   177.2 2352.15   189.1 2346.11   201.1 2334.92   204.6 2332.93
   221.6 2332.51   230.5 2334.86   239.4 2336.05     273  2336.6   283.8 2335.64
     294 2336.62   323.7 2336.12     333 2334.23   345.9 2335.86   350.4 2337.09
   362.9 2344.45   368.1  2346.2   403.7 2349.13   426.2 2361.29     447 2366.28
     460 2370.94   472.9 2371.51   515.2 2386.84   537.8 2393.04   579.1  2410.3
#Mann= 5, -1 ,  0
       0     0.1       0   201.1   0.045       0   230.5     0.1       0
   438.9    0.06       0   468.9     0.1       0
#XS Ineff= 2 , 0
                          291.55         2361.21
Permanent Ineff=
       F       F
Bank Sta=201.1,230.5
XS Rating Curve= 0 ,0
Exp/Cntr(USF)=0,0
Exp/Cntr=0.3,0.1

Type RM Length L Ch R = 1 ,29349   ,426.8,409.4,390.7
BEGIN DESCRIPTION:
Structure XS 4
END DESCRIPTION:
XS GIS Cut Line= 3
2229847.53732681 657731.451582062230260.27091292657691.509622113
2230433.35273936657613.844699994
#Sta/Elev= 30
       0 2420.88    36.8    2403    56.9 2395.28    64.9 2390.03      77 2388.93
    93.1  2381.7   113.2 2377.38   158.4 2359.89   177.5 2347.19   185.9 2337.33
   201.6 2332.35   213.6 2324.51     286 2328.77     294 2326.27   318.5 2327.13
   332.92324.494   338.2 2323.26   350.3 2324.35   362.3 2324.28   374.4 2333.39
   378.4 2334.24   402.5 2334.51   440.9 2348.61   475.9 2356.14   493.5 2365.19
   516.2 2367.29   527.8 2373.94   554.9 2381.31   576.7 2391.87   604.4 2399.74
#Mann= 5, -1 ,  0
       0     0.1       0   332.9   0.045       0   350.3     0.1       0
  424.66    0.06       0  534.66     0.1       0
#XS Ineff= 2 , 0
          317.85 2342.43
Permanent Ineff=
       F       F
Bank Sta=332.9,350.3
XS Rating Curve= 0 ,0
Exp/Cntr(USF)=0,0
Exp/Cntr=0.3,0.1

Type RM Length L Ch R = 1 ,28939   ,83.2,84.4,85.5
BEGIN DESCRIPTION:
Structure XS 3
END DESCRIPTION:
XS GIS Cut Line= 6
2229925.85978117658141.6975893432230178.45864329658127.900172504
2230199.68543842658067.4038063662230203.93079745657997.355382417
2230203.93079745657859.381214032 2230492.6152113657775.535373245
#Sta/Elev= 30
       0  2386.9    26.4 2381.15    42.4 2374.85    66.4 2374.22    98.5 2363.39
   158.6 2348.84   186.6 2344.37   222.6 2329.19   246.7 2322.17   260.1 2320.02
     294 2321.49   327.5 2315.15   339.4  2313.1  353.132315.052   375.4 2317.78
   463.4  2318.9   475.4 2321.36   507.4  2321.2   529.7 2323.34   571.3 2322.04
   583.8  2326.2   630.5 2334.33   696.3 2357.09   712.9 2358.44   721.3 2363.76
   750.4 2374.83   783.7 2385.34   795.1 2391.28   812.9 2393.28   825.9 2400.45
#Mann= 7, -1 ,  0
       0     0.1       0     250    0.05       0  302.98     0.1       0
   327.5   0.045       0  353.13     0.1       0  595.24    0.06       0
  785.24     0.1       0
Bank Sta=327.5,353.13
XS Rating Curve= 0 ,0
Exp/Cntr(USF)=0,0
Exp/Cntr=0.3,0.1

Type RM Length L Ch R = 1 ,28855   ,281.1,295.2,305.7
BEGIN DESCRIPTION:
Structure XS 2
END DESCRIPTION:
XS GIS Cut Line= 6
2229941.77987752658206.4393145082230249.56840699 658192.64189767
2230278.22458043658094.998640043  2230288.837978658007.968779985
2230283.53127921657891.221406737 2230507.4739679657815.866284003
#Sta/Elev= 30
       0 2383.79    26.5 2376.24    50.4 2373.68    66.5 2368.07   106.5 2359.52
   138.5 2348.68   174.6 2342.22   214.6 2331.89   222.6  2332.3   250.6 2321.68
   278.7 2321.81   290.7 2316.29   315.9 2314.69   418.9 2312.97     424 2311.61
   431.8 2309.98   445.6 2311.57   478.5 2316.95   504.3 2316.55   569.8 2319.65
   640.4 2326.97   699.5 2342.23   737.5 2357.83   750.1 2358.72   758.6 2364.28
   783.9 2375.01   793.4 2376.13   821.5 2387.43   834.5 2394.91   850.7 2398.64
#Mann= 6, -1 ,  0
       0     0.1       0     230    0.05       0     424   0.045       0
   445.6     0.1       0   634.4    0.06       0   804.4     0.1       0
#XS Ineff= 2 , 0
          418.05 2333.62
Permanent Ineff=
       F       F
Bank Sta=424,445.6
XS Rating Curve= 0 ,0
Exp/Cntr(USF)=0,0
Exp/Cntr=0.3,0.1

Type RM Length L Ch R = 1 ,28560   ,304.3,303.9,302.6
BEGIN DESCRIPTION:
Structure XS 1
END DESCRIPTION:
XS GIS Cut Line= 2
2230111.59806201658414.9028967052230686.31848569658193.003119223
#Sta/Elev= 30
       0 2374.14    26.3 2362.62    39.2 2358.73    73.5 2334.49   116.2 2331.75
   150.7 2326.54     155 2325.35   172.1 2313.64     185 2309.85   205.9 2308.92
   233.8  2309.9   270.4  2308.5   283.6 2309.81   335.9 2309.25   347.9 2308.38
   356.5 2306.53  382.63 2304.77   388.5 2303.36   397.7 2302.99   403.7  2303.1
     408 2304.72   420.8 2311.36   446.5 2331.21   459.4 2339.22   471.2 2344.51
   523.7 2359.06     549 2363.66   562.3 2368.98   579.5 2370.78   616.1 2379.79
#Mann= 6, -1 ,  0
       0     0.1       0      60    0.05       0     170     0.1       0
  382.63   0.045       0     408     0.1       0     590    0.06       0
#XS Ineff= 2 , 0
          371.87 2312.39
Permanent Ineff=
       F       F
Bank Sta=382.63,408
XS Rating Curve= 0 ,0
Exp/Cntr(USF)=0,0
Exp/Cntr=0.3,0.1