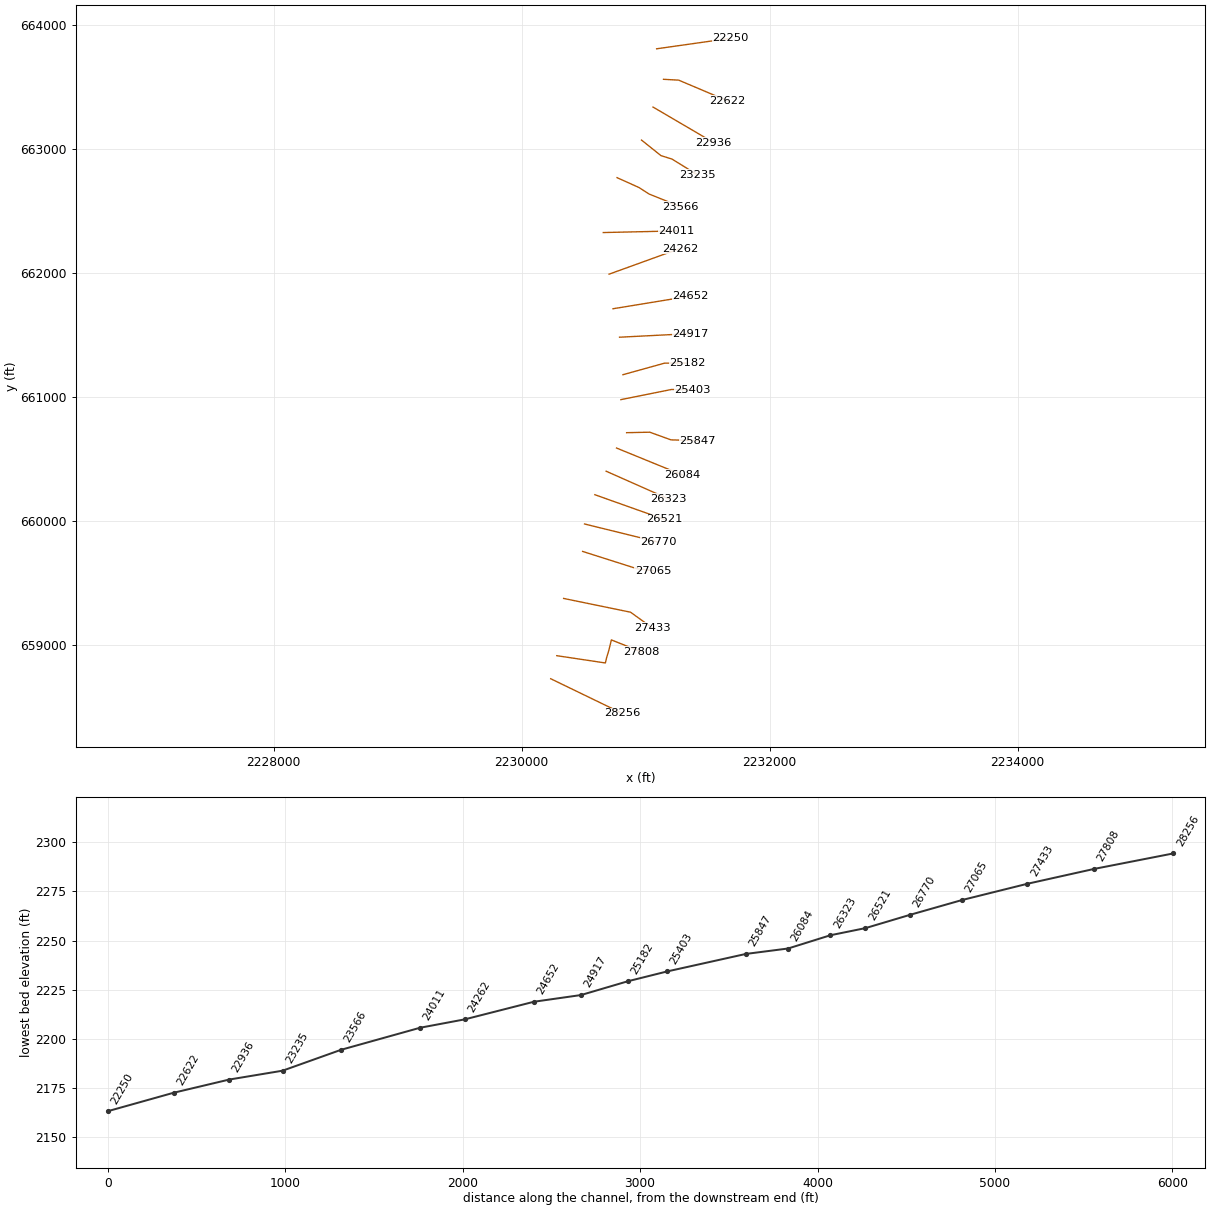
HEC-RAS study LONGRN.prj: LONGRN

--- LONGRN.g01 (geometry) --- (continued)

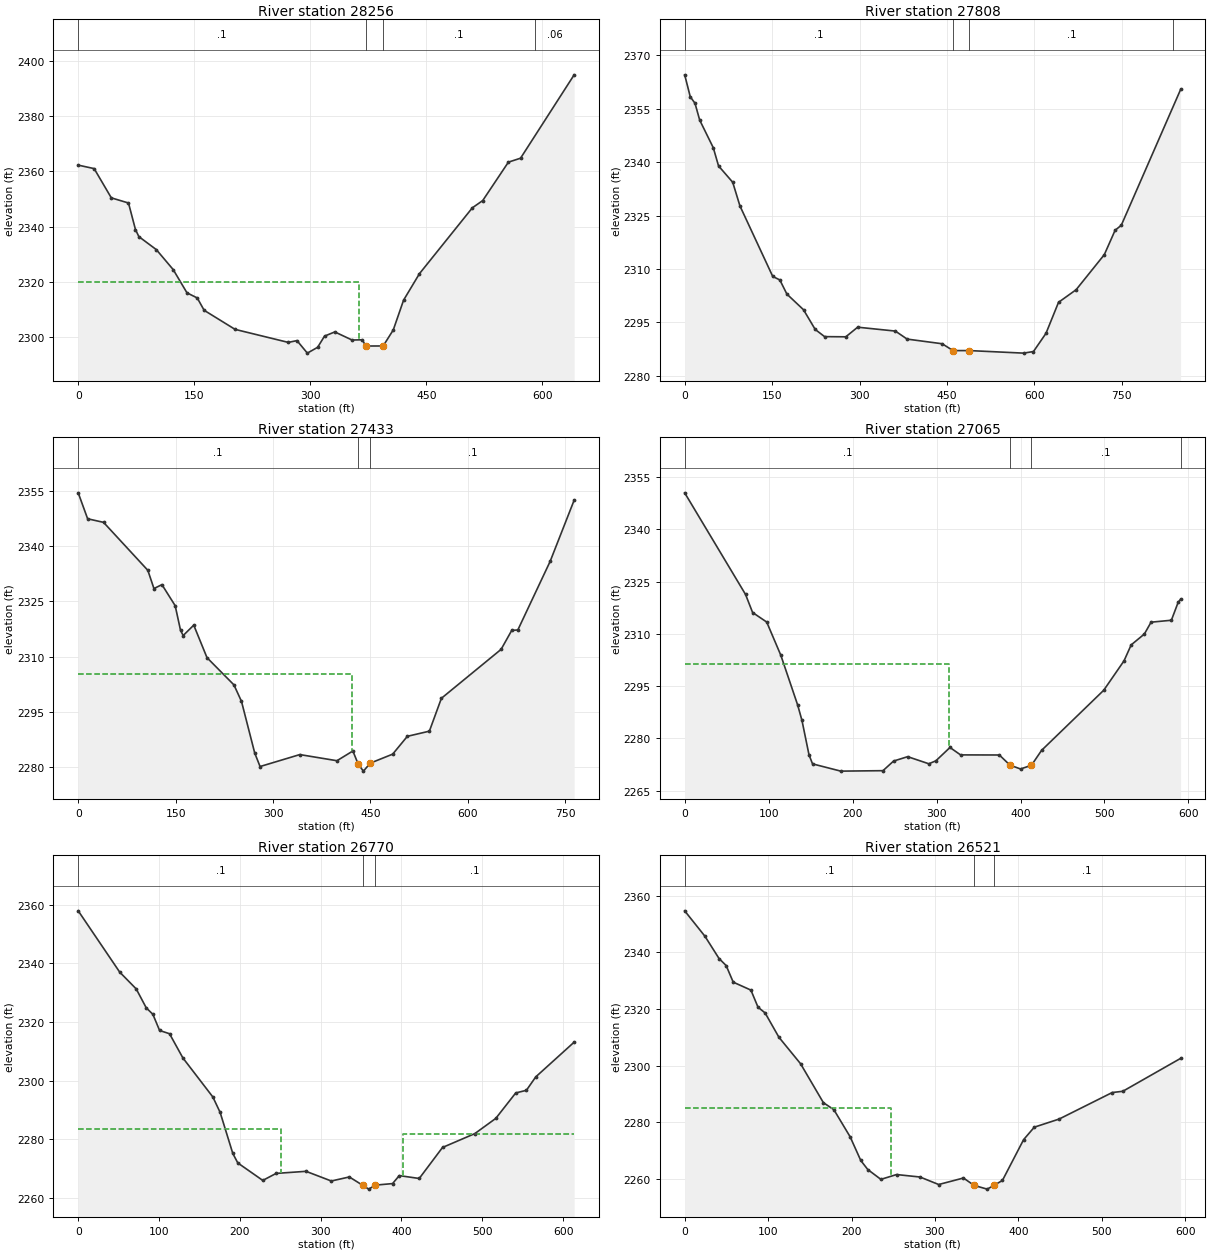
Type RM Length L Ch R = 1 ,28256   ,424.1,447.7,467.7
XS GIS Cut Line= 2
2230233.64293963 658725.562585182230810.58236108658445.968865552
#Sta/Elev= 30
       0 2362.29    20.6 2361.03    42.8 2350.45      65 2348.59      74    2339
    78.4 2336.43     101 2331.72   122.8  2324.5   140.6  2316.1   153.9 2314.24
   162.8 2309.78   202.8 2302.88   271.6 2298.17   282.8 2298.82   296.2 2294.29
   309.5  2296.4   318.4 2300.44   331.7 2301.96     354 2299.03   367.3 2299.11
   371.7 2296.86  394.21 2296.88   407.3 2302.69   420.6 2313.45   441.1 2323.02
   509.5 2346.85   522.9 2349.47   556.1 2363.37   571.8 2364.79   641.1 2394.95
#Mann= 4, -1 ,  0
       0     0.1       0   371.7   0.045       0  394.21     0.1       0
     590    0.06       0
#XS Ineff= 2 , 0
          363.55 2319.99
Permanent Ineff=
       F       F
Bank Sta=371.7,394.21
XS Rating Curve= 0 ,0
Exp/Cntr(USF)=0,0
Exp/Cntr=0.3,0.1

Type RM Length L Ch R = 1 ,27808   ,393.9,375.4,357.8
XS GIS Cut Line= 6
2230282.69048949658911.5257541662230674.49357214658852.821851695
2230684.03010561658893.8729125232230702.64340785658955.353213848
2230722.94882847659038.8310541792230966.73636528658941.697211065
#Sta/Elev= 30
       0 2364.51     9.6 2358.35    17.7 2356.53    25.8 2351.79    49.1 2344.04
    58.1 2338.94    82.4 2334.36    94.8 2327.72   151.1 2307.92   163.3 2306.93
   175.4 2302.96   203.9 2298.57     224 2293.03   240.1 2291.02   276.5 2290.97
   296.8 2293.67   361.5 2292.58   381.7 2290.33   441.8 2289.02  460.57  2287.1
  488.732287.102   581.6 2286.39   598.5 2286.84     620 2291.95   641.5 2300.65
   671.7 2304.19   720.1 2314.04   738.6 2320.88   749.2 2322.28     851  2360.4
#Mann= 4, -1 ,  0
       0     0.1       0  460.57   0.045       0  488.73     0.1       0
  838.55    0.06       0
Bank Sta=460.57,488.73
XS Rating Curve= 0 ,0
Exp/Cntr(USF)=0,0
Exp/Cntr=0.3,0.1

Type RM Length L Ch R = 1 ,27433   ,369,368.1,366.8
XS GIS Cut Line= 3
2230337.93583504659373.5099354282230877.15229433659262.560046687
2231050.23412076659138.296171297
#Sta/Elev= 30
       0 2354.55    14.5 2347.49      39 2346.52   107.2 2333.47   116.6 2328.51
   128.9 2329.58   149.3 2323.85   157.5 2317.19   161.6 2315.73   177.9 2318.56
   198.3 2309.71   239.8  2302.3   251.4 2297.82   271.8 2283.76     280  2280.1
   341.2 2283.35   398.4 2281.68   422.9 2284.33  431.082280.753   439.1 2278.85
   449.8 2281.03   484.2 2283.47   506.8 2288.32   540.7 2289.72   559.2 2298.66
   651.1 2311.97   667.5 2317.13   676.9 2317.25   726.6 2335.89   763.6 2352.55
#Mann= 3, -1 ,  0
       0     0.1       0  431.08   0.045       0   449.8     0.1       0
#XS Ineff= 2 , 0
          421.08 2305.34
Permanent Ineff=
       F       F
Bank Sta=431.08,449.8
XS Rating Curve= 0 ,0
Exp/Cntr(USF)=0,0
Exp/Cntr=0.3,0.1

Type RM Length L Ch R = 1 ,27065   ,285.5,294.2,292.8
XS GIS Cut Line= 3
2230491.04668151659752.9585549222230930.40824092659613.161695109
2231059.11011186659597.628710685
#Sta/Elev= 30
       0 2350.47    72.5  2321.3    80.9 2316.12    97.7 2313.38   114.5 2303.86
   134.5 2289.62   139.7 2285.14   148.1 2275.25   152.3 2272.67   185.9 2270.59
   236.2 2270.72   248.8 2273.48   265.6 2274.74   290.8  2272.7   299.2 2273.55
     316 2277.38   328.6 2275.25   374.8 2275.22   387.4 2272.32     400 2271.21
  413.032272.264   425.1 2276.55   499.1  2293.8   523.3 2302.25   531.8 2306.82
   547.5 2309.94   555.5 2313.34   579.7  2313.9   587.7    2319   590.7 2319.93
#Mann= 4, -1 ,  0
       0     0.1       0   387.4   0.045       0  413.03     0.1       0
   590.7    0.06       0
#XS Ineff= 2 , 0
          314.95 2301.38
Permanent Ineff=
       T       F
Bank Sta=387.4,413.03
XS Rating Curve= 0 ,0
Exp/Cntr(USF)=0,0
Exp/Cntr=0.3,0.1

Type RM Length L Ch R = 1 ,26770   ,248.3,249.8,247.4
XS GIS Cut Line= 2
2230506.40737754659974.3916118812231102.31898514659827.822905556
#Sta/Elev= 30
       0 2357.92    51.3 2337.04    71.8 2331.29    84.2 2324.84    92.4 2322.64
   100.7 2317.13     113 2316.02   129.5 2307.78   166.6 2294.46   175.6 2289.21
   191.3  2275.2   197.5 2271.96   228.4 2266.01   244.9  2268.4   281.9 2269.11
   313.2 2265.81   335.5 2267.19     352 2264.36   359.5 2263.04  367.642264.399
     389 2264.93   397.3 2267.65     422 2266.67   450.8 2277.24   490.8 2281.97
   516.7 2287.15   541.4 2295.83   554.6 2296.73   566.2 2301.31   613.7 2313.15
#Mann= 3, -1 ,  0
       0     0.1       0     352   0.045       0  367.64     0.1       0
#XS Ineff= 2 , 0
          251.19 2283.62  401.81          2281.9
Permanent Ineff=
       F       F
Bank Sta=352,367.64
XS Rating Curve= 0 ,0
Exp/Cntr(USF)=0,0
Exp/Cntr=0.3,0.1

Type RM Length L Ch R = 1 ,26521   ,196,197.6,194
XS GIS Cut Line= 2
2230589.32435082660210.7067411752231149.45570698660011.476346272
#Sta/Elev= 30
       0 2354.65    24.3 2345.66    41.2  2337.8    49.7 2335.32    58.2 2329.45
    79.4 2326.64    87.9  2320.6    96.4 2318.58     113 2309.97   138.9 2300.63
   166.3 2286.86   178.8 2284.41   198.3 2274.83   211.1 2266.44   219.5 2263.24
   235.2 2259.77     254 2261.47   282.1  2260.6   304.5 2257.95   334.2 2260.25
   346.9 2257.64   362.6 2256.32  370.622257.618   380.9 2259.39   406.3 2273.81
   419.1 2278.21   448.8 2281.07   512.5 2290.45   525.2 2290.89   594.5 2302.52
#Mann= 3, -1 ,  0
       0     0.1       0   346.9   0.045       0  370.62     0.1       0
#XS Ineff= 2 , 0
           247.8  2284.9
Permanent Ineff=
       F       F
Bank Sta=346.9,370.62
XS Rating Curve= 0 ,0
Exp/Cntr(USF)=0,0
Exp/Cntr=0.3,0.1

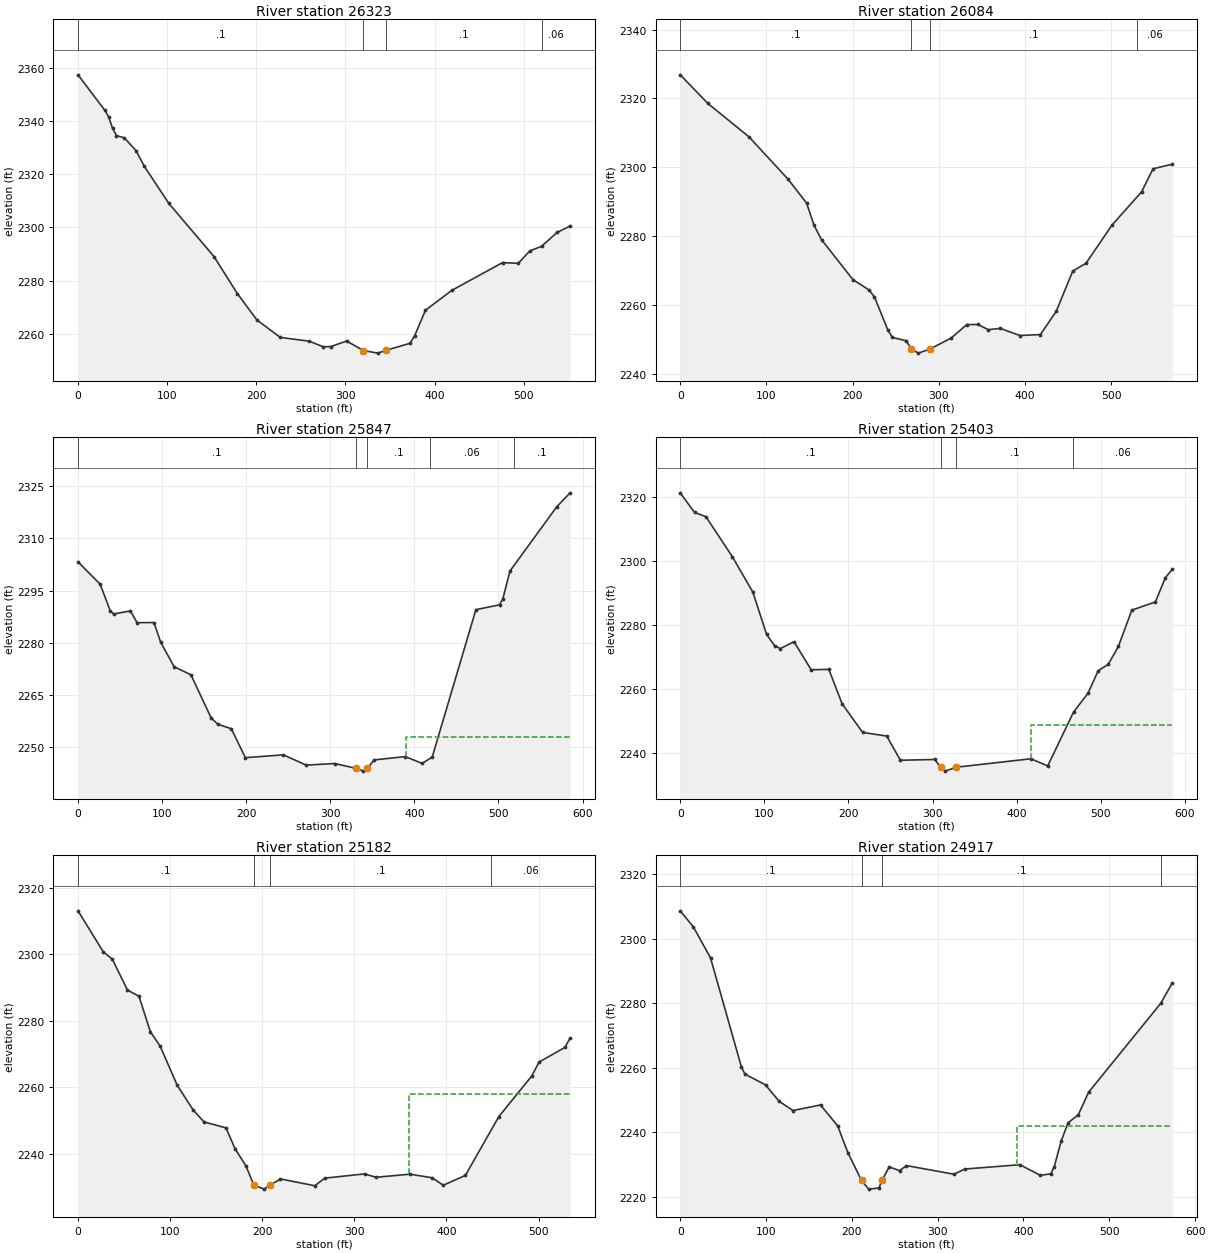
Type RM Length L Ch R = 1 ,26323   ,237.8,238.8,239.5
XS GIS Cut Line= 2
2230680.77436815660400.138919936 2231185.3824995660176.412984675
#Sta/Elev= 30
       0 2357.38      30 2344.07    34.3 2341.62    38.7 2337.34    43.1 2334.52
    51.9 2333.69      65 2328.91    74.5 2322.91   101.8 2309.05   152.5 2289.03
   178.7 2275.12   200.6  2265.2   226.9  2258.6   259.5 2257.19     275 2255.07
   283.8 2255.16   301.3 2257.25   320.1 2253.67   336.3 2252.69     345 2253.68
   372.5  2256.4   377.7 2259.27   389.8 2268.84   419.4 2276.31   476.3 2286.76
   493.8 2286.46   506.9 2291.15     520 2292.87   537.5 2298.11     552 2300.48
#Mann= 4, -1 ,  0
       0     0.1       0   320.1   0.045       0     345     0.1       0
     520    0.06       0
Bank Sta=320.1,345
XS Rating Curve= 0 ,0
Exp/Cntr(USF)=0,0
Exp/Cntr=0.3,0.1

Type RM Length L Ch R = 1 ,26084   ,240,237.1,237.5
XS GIS Cut Line= 2
2230764.40623593660587.3599947372231292.86396964660371.243265975
#Sta/Elev= 30
       0 2326.88    32.1 2318.56    79.7 2308.86   125.1 2296.54   146.7 2289.56
   155.3 2283.11     164 2278.93   200.3 2267.34   219.3 2264.28   225.4 2262.27
   240.7 2252.81   246.1 2250.53   262.2 2249.55   268.3 2247.12   276.3 2245.95
   289.8 2247.15   314.4 2250.33   332.5 2254.26   345.5 2254.28   357.3 2252.77
   371.4 2253.14   394.1 2251.07   417.9 2251.35   436.2 2258.07   455.4 2269.79
   470.8 2272.09   501.1 2283.23   535.2 2292.82   548.6 2299.56   570.9 2300.89
#Mann= 4, -1 ,  0
       0     0.1       0   268.3   0.045       0   289.8     0.1       0
     530    0.06       0
Bank Sta=268.3,289.8
XS Rating Curve= 0 ,0
Exp/Cntr(USF)=0,0
Exp/Cntr=0.3,0.1

Type RM Length L Ch R = 1 ,25847   ,441.4,444.3,446.5
XS GIS Cut Line= 4
2230845.89362697660711.2098427842231032.89325384660715.122645238
2231203.05538153660653.3691026292231420.06263636660646.443864139
#Sta/Elev= 30
       0 2303.28    26.3 2296.88    38.3 2289.27    42.3 2288.33    62.3  2289.2
    70.3 2285.82    90.3 2285.87    98.3 2280.22   114.3 2273.18   134.3 2270.86
   158.3 2258.49   166.3 2256.65   182.3 2255.38     199 2247.06   244.2 2247.87
   271.4 2244.93   305.4 2245.38     331 2243.98   339.5  2243.2   344.1 2243.99
   352.2 2246.42   389.2 2247.37   409.2 2245.42   421.2 2247.21   473.2 2289.56
   501.3 2290.96   505.3 2292.72   513.7 2300.66   569.3 2319.09   585.2 2323.11
#Mann= 5, -1 ,  0
       0     0.1       0     331   0.045       0   344.1     0.1       0
  418.06    0.06       0  518.06     0.1       0
#XS Ineff= 2 , 0
                          389.59         2253.09
Permanent Ineff=
       F       F
Bank Sta=331,344.1
XS Rating Curve= 0 ,0
Exp/Cntr(USF)=0,0
Exp/Cntr=0.3,0.1

Type RM Length L Ch R = 1 ,25403   ,221,221,222.7
XS GIS Cut Line= 3
2230799.48737221660977.8453266242231208.33171944661060.027293797
2231376.23605469661054.747292893
#Sta/Elev= 30
       0 2321.44      17 2315.31    30.6 2313.96    61.9 2301.47    86.4 2290.32
   102.7 2277.08   112.1 2273.61     119 2272.65   135.3 2274.82   155.7 2266.03
   176.7 2266.16   192.5 2255.36   216.9 2246.41   245.5 2245.28   261.8  2237.7
   302.6 2237.94   309.6 2235.51   314.9 2234.29   328.12235.513   416.9 2238.16
   436.9 2235.93   467.6 2252.76   484.9 2258.73   496.9 2265.71     509 2267.77
   520.9 2273.32   536.9  2284.7   564.9 2287.27   576.9 2294.91     585 2297.48
#Mann= 4, -1 ,  0
       0     0.1       0   309.6   0.045       0   328.1     0.1       0
  467.02    0.06       0
#XS Ineff= 2 , 0
                           417.1         2248.67
Permanent Ineff=
       F       F
Bank Sta=309.6,328.1
XS Rating Curve= 0 ,0
Exp/Cntr(USF)=0,0
Exp/Cntr=0.3,0.1

Type RM Length L Ch R = 1 ,25182   ,266.3,264.5,263.3
XS GIS Cut Line= 3
2230816.39790735661179.1719849642231152.13324035661272.323252604
 2231337.9252516661272.960459263
#Sta/Elev= 30
       0 2313.08    27.4 2300.75    37.2 2298.54    53.7 2289.23    66.2 2287.36
    78.6 2276.64    89.2 2272.34   107.7 2260.57   124.9 2253.17   136.8 2249.54
   160.7 2247.74   170.4  2241.5   182.4 2236.26   190.82230.555     202 2229.31
   208.32230.469   219.8 2232.38   257.1 2230.33   267.9 2232.62   311.1 2233.89
   323.6 2232.88   360.5 2233.81   384.5 2232.72   396.5 2230.48   420.5 2233.43
   456.9 2251.17   492.5 2263.32   500.5 2267.56   528.5 2271.95   534.2 2274.77
#Mann= 4, -1 ,  0
       0     0.1       0   190.8   0.045       0   208.3     0.1       0
  448.42    0.06       0
#XS Ineff= 2 , 0
                          359.57         2257.93
Permanent Ineff=
       F       F
Bank Sta=190.8,208.3
XS Rating Curve= 0 ,0
Exp/Cntr(USF)=0,0
Exp/Cntr=0.3,0.1

Type RM Length L Ch R = 1 ,24917   ,263.1,264.9,266.1
XS GIS Cut Line= 2
2230788.89786792661481.6724186222231361.54574768661510.790107423
#Sta/Elev= 30
       0  2308.7    15.3 2303.72    35.3  2294.1    71.4 2260.15    75.4 2258.01
    99.4 2254.66   115.4 2249.53   131.4 2246.69   163.5 2248.43   183.5 2241.93
   195.5 2233.53  211.272225.009   219.6 2222.29   231.6 2222.64   235.1 2225.02
   243.6  2229.2   255.6 2228.01   263.6  2229.6     319 2226.92   331.7 2228.53
   395.8 2229.87   419.8 2226.56   431.8 2227.05   435.8 2229.18   443.8 2237.13
   451.9 2242.85   463.9 2245.38   475.9 2252.38     560 2279.99   573.4 2286.29
#Mann= 4, -1 ,  0
       0     0.1       0  211.27   0.045       0   235.1     0.1       0
     560    0.06       0
#XS Ineff= 2 , 0
                          392.57         2241.98
Permanent Ineff=
       F       F
Bank Sta=211.27,235.1
XS Rating Curve= 0 ,0
Exp/Cntr(USF)=0,0
Exp/Cntr=0.3,0.1

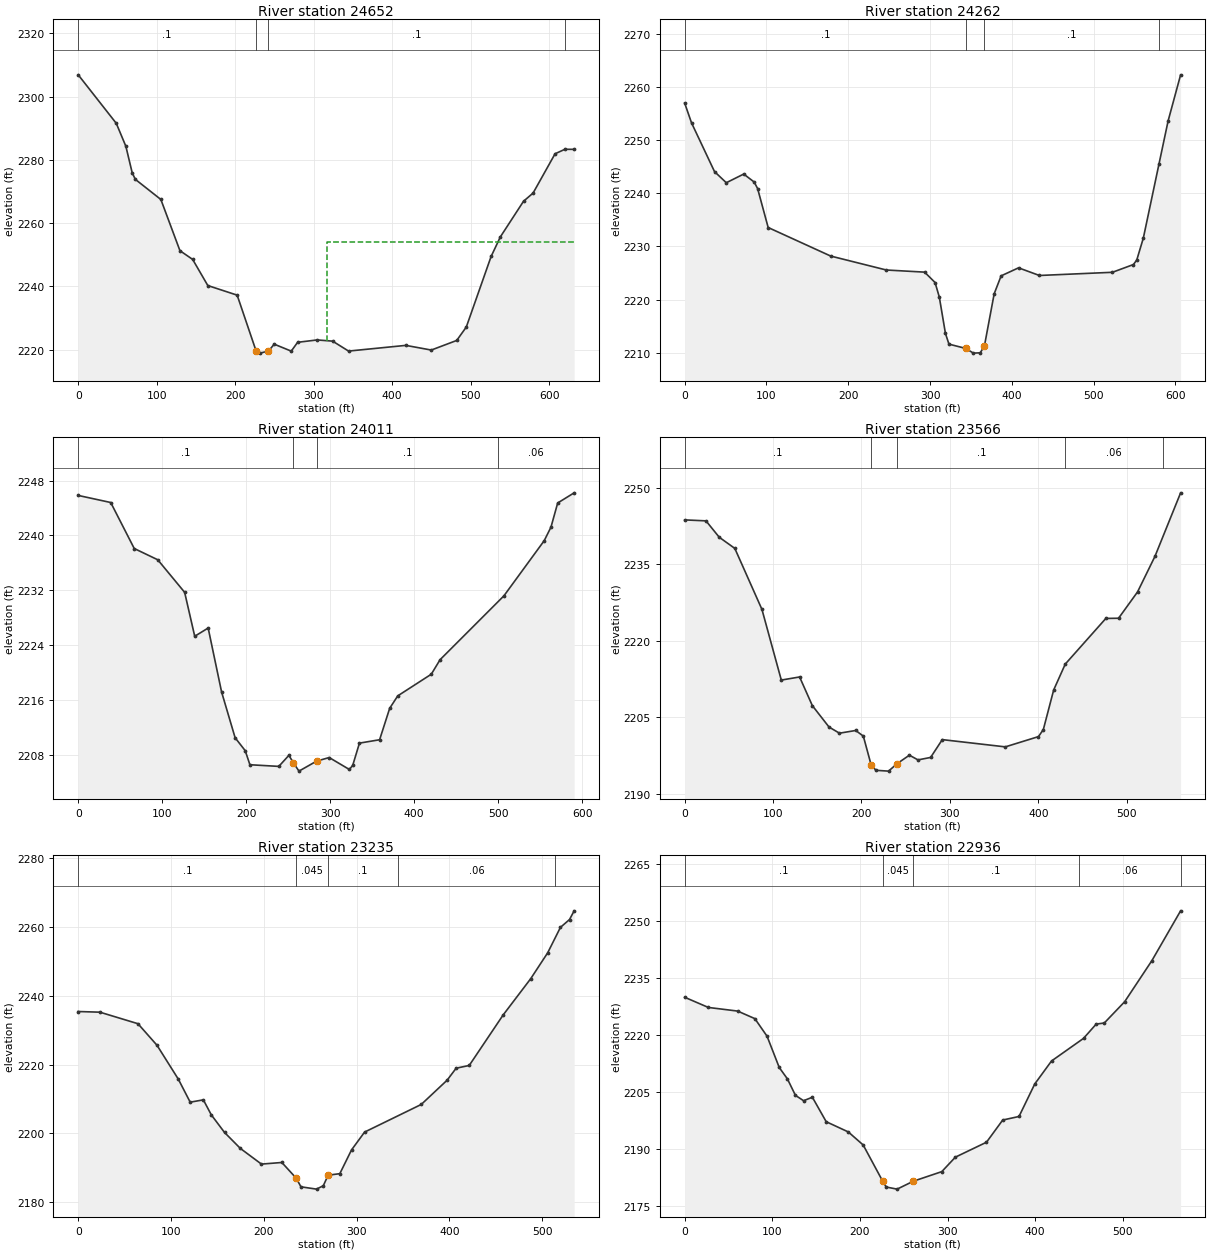
Type RM Length L Ch R = 1 ,24652   ,385.1,390,392.8
XS GIS Cut Line= 2
2230736.30237134661711.4253149562231359.84074606661813.499212598
#Sta/Elev= 30
       0 2306.89    48.5 2291.55    60.7  2284.3    68.8 2275.89    72.8 2273.83
   105.3 2267.47   129.6 2251.28   145.8 2248.52   165.1 2240.26   202.5 2237.22
   226.7 2219.51   231.3 2218.89  242.36 2219.52   249.7 2221.72   271.4 2219.52
   279.5 2222.31   304.4 2223.06   324.1 2222.68   344.4 2219.54   417.4 2221.34
   449.8 2219.86   482.2  2222.9   494.4 2227.14     526 2249.45   537.8 2255.65
   567.3 2266.91   579.5 2269.51   607.5 2281.93     620 2283.34   631.8 2283.33
#Mann= 4, -1 ,  0
       0     0.1       0   226.7   0.045       0  242.36     0.1       0
     620    0.06       0
#XS Ineff= 2 , 0
                          316.33          2253.9
Permanent Ineff=
       F       F
Bank Sta=226.7,242.36
XS Rating Curve= 0 ,0
Exp/Cntr(USF)=0,0
Exp/Cntr=0.3,0.1

Type RM Length L Ch R = 1 ,24262   ,253.8,251.2,244.3
XS GIS Cut Line= 2
2230704.27374295661990.3351650612231274.55617108662196.701958119
#Sta/Elev= 30
       0 2256.94     8.4 2253.22    36.5 2244.06    50.9 2241.97    72.2  2243.6
      85  2242.1    89.2 2240.87   102.1 2233.55   178.6 2228.18   246.6 2225.56
   293.4 2225.16   306.2 2223.21   311.4 2220.47   318.9 2213.63   323.2 2211.62
     3442210.804     353 2209.93   361.4 2209.99   366.52211.228   378.5 2221.09
     387 2224.46   408.3 2225.97   433.8 2224.53   523.1 2225.13   548.8 2226.59
   552.9 2227.45   560.9 2231.56     580 2245.46   591.2 2253.59   606.5 2262.26
#Mann= 4, -1 ,  0
       0     0.1       0     344   0.045       0   366.5     0.1       0
     580    0.06       0
Bank Sta=344,366.5
XS Rating Curve= 0 ,0
Exp/Cntr(USF)=0,0
Exp/Cntr=0.3,0.1

Type RM Length L Ch R = 1 ,24011   ,453.2,445.3,436.6
XS GIS Cut Line= 2
2230657.47151462662326.2395534112231247.72492272 662339.55354006
#Sta/Elev= 30
       0 2245.83    38.7  2244.8    66.7  2238.1    94.7 2236.46   126.7 2231.72
   138.7 2225.32   154.7 2226.52   170.7  2217.2   186.8 2210.54   198.8 2208.66
   204.4 2206.61   238.8 2206.37   250.8 2207.98   256.12206.905   262.8 2205.68
   283.72207.131   298.8 2207.66   322.8 2205.92   326.8 2206.52   334.8 2209.76
   358.8 2210.25   370.8 2214.83   380.4 2216.64   420.3 2219.79   430.8 2221.91
   506.8 2231.21   554.8 2239.25   562.8 2241.21   570.8 2244.73   590.4 2246.21
#Mann= 4, -1 ,  0
       0     0.1       0   256.1   0.045       0   283.7     0.1       0
     500    0.06       0
Bank Sta=256.1,283.7
XS Rating Curve= 0 ,0
Exp/Cntr(USF)=0,0
Exp/Cntr=0.3,0.1

Type RM Length L Ch R = 1 ,23566   ,327.2,330.4,337.2
XS GIS Cut Line= 4
2230768.51324056662769.4576733862230945.97200399 662689.42440936
2231026.60444592662637.476337526 2231277.2823955662536.104247315
#Sta/Elev= 30
       0 2243.67    24.1 2243.48    39.1 2240.27    56.7 2238.09    87.4 2226.14
   109.3  2212.3     130 2212.91   144.4  2207.3   163.3  2203.1   175.1  2201.9
   193.5 2202.43   202.1 2201.32   210.82195.761   216.3 2194.63   230.6 2194.47
   240.42195.948   254.2 2197.59   263.9 2196.67   278.2 2197.15   291.4 2200.64
   362.7 2199.22   400.2 2201.23   405.7 2202.61   417.4 2210.36   430.5 2215.43
   476.4 2224.37   490.8 2224.41   512.3 2229.57     532 2236.54     561 2248.97
#Mann= 5, -1 ,  0
       0     0.1       0   210.8   0.045       0   240.4     0.1       0
  430.59    0.06       0  540.59     0.1       0
Bank Sta=210.8,240.4
XS Rating Curve= 0 ,0
Exp/Cntr(USF)=0,0
Exp/Cntr=0.3,0.1

Type RM Length L Ch R = 1 ,23235   ,304.5,299.9,296.6
XS GIS Cut Line= 4
2230965.91220532663072.5792260562231122.89586321662946.965840034
2231211.88516887662919.1849146612231416.36875361662792.985506429
#Sta/Elev= 30
       0 2235.42    23.4 2235.23    64.4 2231.88    84.9 2225.63   107.9 2215.78
   120.7 2209.09   134.9 2209.76   143.5 2205.39   157.7  2200.3   174.8 2195.65
   197.5  2191.1   219.5 2191.57   235.1 2186.98   240.1  2184.5   256.9 2183.83
   264.2 2184.82   269.4 2187.88     282 2188.32   294.6 2195.21   308.7  2200.4
   369.8 2208.43   397.7 2215.48   407.4 2218.96   421.5 2219.75     458  2234.4
   487.8 2244.97   506.1 2252.49   519.8 2259.86   529.6 2262.14   534.6 2264.67
#Mann= 5, -1 ,  0
       0     0.1       0   235.1   0.045       0   269.4     0.1       0
  344.28    0.06       0  514.28     0.1       0
Bank Sta=235.1,269.4
XS Rating Curve= 0 ,0
Exp/Cntr(USF)=0,0
Exp/Cntr=0.3,0.1

Type RM Length L Ch R = 1 ,22936   ,311,313.4,315.1
XS GIS Cut Line= 2
2231059.11011186663338.8589590352231547.28962232663052.608246083
#Sta/Elev= 30
       0 2229.86      27 2227.18    60.5 2226.22    80.1 2224.23      94  2219.6
   107.9 2211.37   117.2 2208.38   126.4 2204.03   135.7 2202.62   145.7 2203.54
   161.5 2197.09   186.7  2194.4   203.7 2190.96  225.962181.427     230 2179.89
   242.4 2179.34   260.9 2181.42   293.4 2183.95   308.9 2187.76   344.4 2191.69
   362.9 2197.53   381.5 2198.47   399.5 2207.04   418.6 2213.08   455.1 2219.03
   469.6  2222.8   478.8 2223.08     502 2228.67   533.2 2239.53   565.9 2252.62
#Mann= 5, -1 ,  0
       0     0.1       0  225.96   0.045       0   260.9     0.1       0
     450    0.06       0  565.91     0.1       0
Bank Sta=225.96,260.9
XS Rating Curve= 0 ,0
Exp/Cntr(USF)=0,0
Exp/Cntr=0.3,0.1

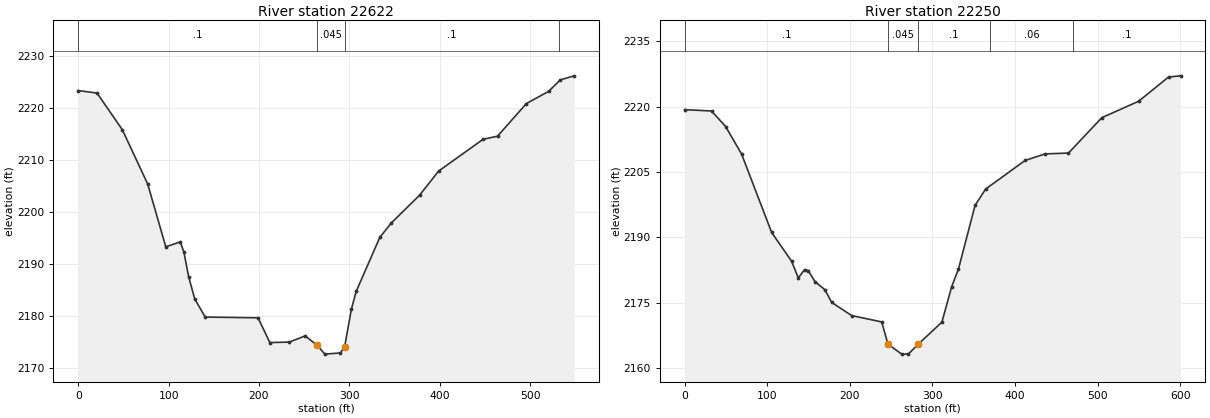
Type RM Length L Ch R = 1 ,22622   ,362.5,372,378
XS GIS Cut Line= 3
 2231143.4320273663562.9777342922231265.47690492663556.320740968
2231658.23951106663389.895907856
#Sta/Elev= 30
       0 2223.31    20.8 2222.84    48.8 2215.79    76.9 2205.34    96.9 2193.27
   112.9  2194.2   116.9 2192.29   122.2 2187.52   128.9 2183.26   140.5 2179.76
     199 2179.61   212.1 2174.85   233.8 2174.95   251.1 2176.14   264.6  2174.3
   272.9 2172.63   290.2 2172.86  294.882174.093   302.3 2181.28   307.6 2184.69
   333.7 2195.06   346.4 2197.84   377.7 2203.18   398.8 2207.83   448.1 2213.95
     464 2214.54   495.9 2220.81   520.5 2223.16   533.5 2225.37   548.8 2226.15
#Mann= 4, -1 ,  0
       0     0.1       0   264.6   0.045       0  294.88     0.1       0
  532.23    0.06       0
Bank Sta=264.6,294.88
XS Rating Curve= 0 ,0
Exp/Cntr(USF)=0,0
Exp/Cntr=0.3,0.1

Type RM Length L Ch R = 1 ,22250   ,369.3,368.7,367.2
XS GIS Cut Line= 2
2231087.95708293663809.2864872972231682.64848658663893.608402741
#Sta/Elev= 30
       0 2219.32    32.5 2219.01    49.6 2215.45    68.9 2209.14   105.3 2191.15
   129.5 2184.54   137.6  2180.7   145.2 2182.63   149.7 2182.38   157.8 2179.88
   169.9 2177.98     178  2175.1   202.2 2172.08   238.6 2170.62  246.152165.536
   262.8 2163.23   270.9 2163.25   282.8  2165.5   311.5 2170.57   323.4 2178.74
   331.5 2182.71   351.7 2197.37   364.5 2201.11   412.3 2207.66   436.5 2209.17
   464.8 2209.36   505.2 2217.48   549.7 2221.24     586 2226.81   600.6 2227.08
#Mann= 5, -1 ,  0
       0     0.1       0  246.15   0.045       0   282.8     0.1       0
     370    0.06       0     470     0.1       0
Bank Sta=246.15,282.8
XS Rating Curve= 0 ,0
Exp/Cntr(USF)=0,0
Exp/Cntr=0.3,0.1