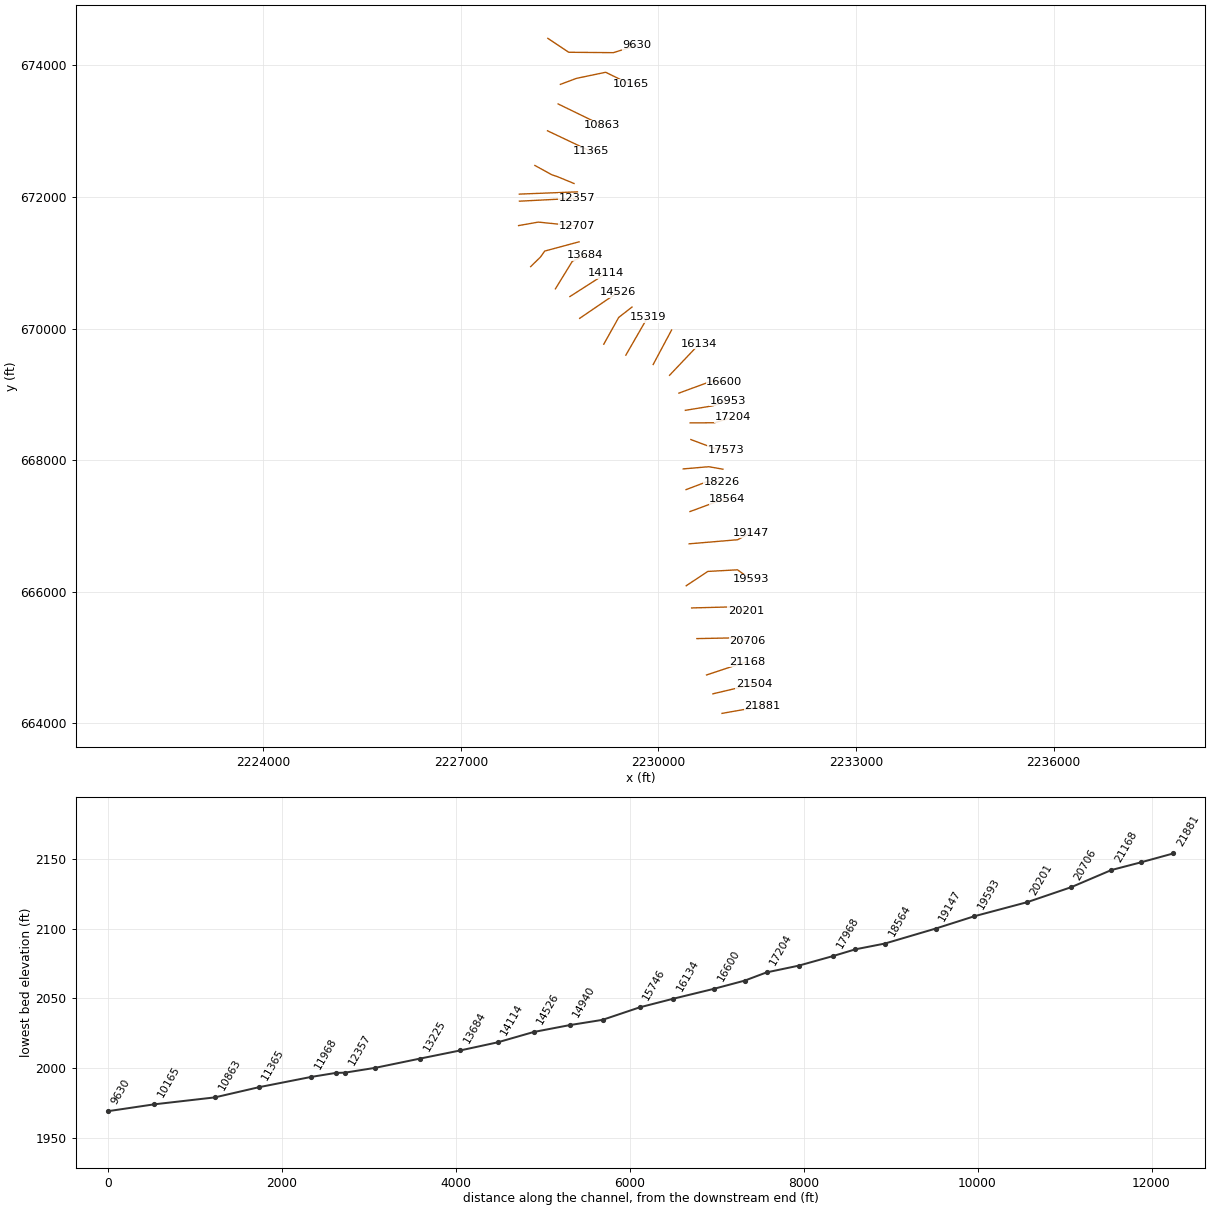
HEC-RAS study LONGRN.prj: LONGRN

--- LONGRN.g01 (geometry) --- (continued)

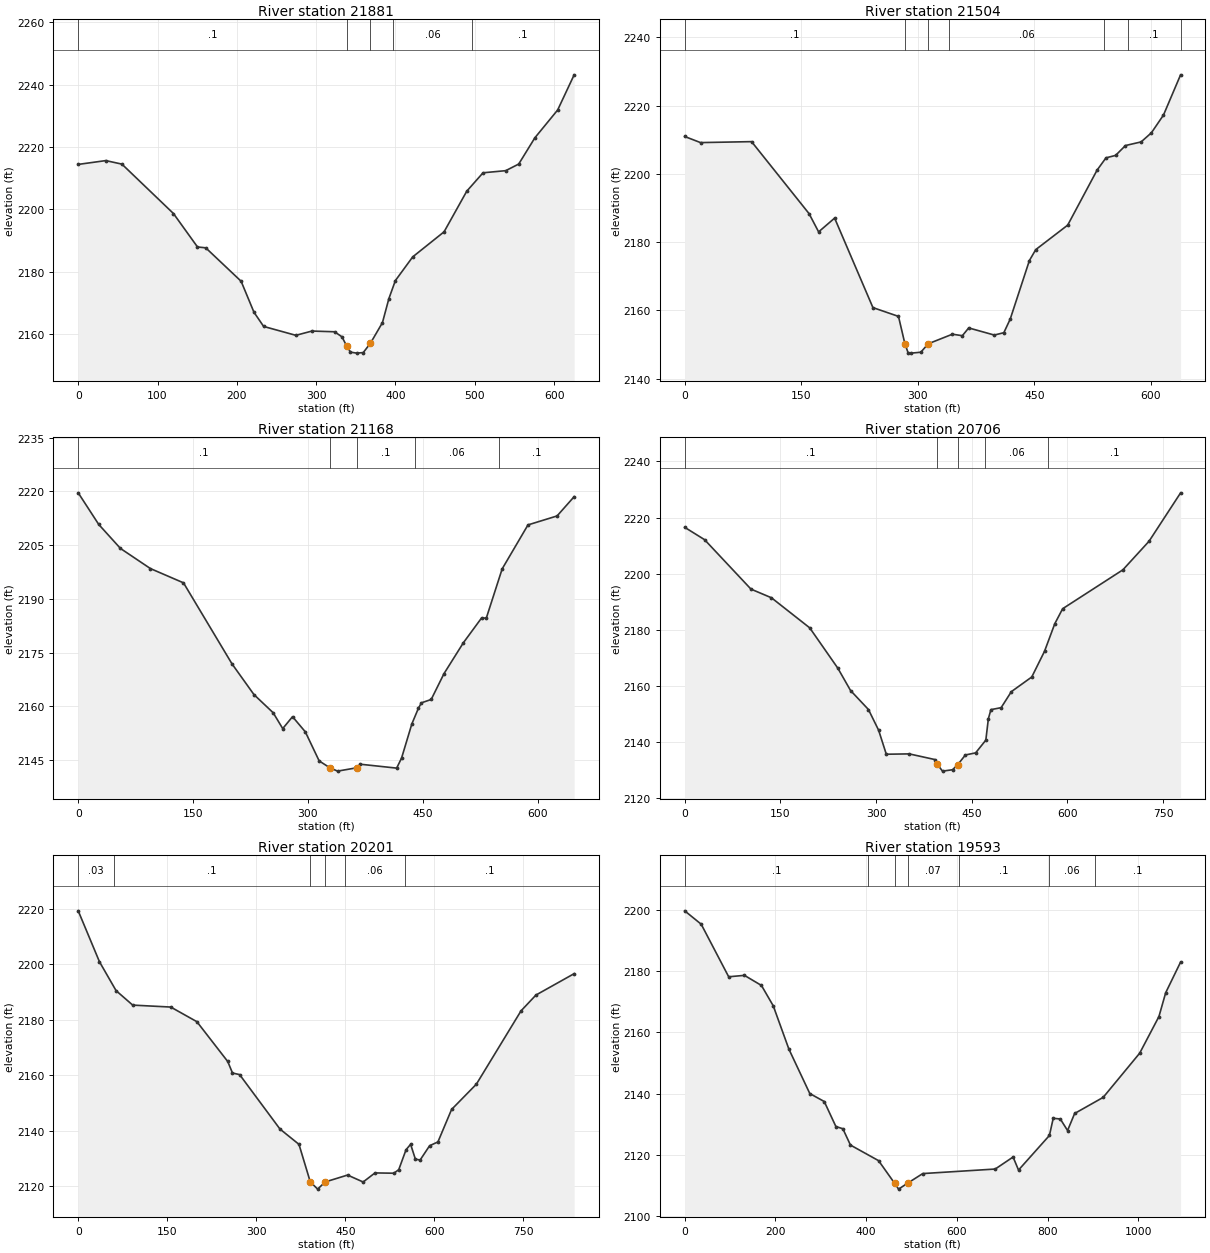
Type RM Length L Ch R = 1 ,21881   ,372.1,377,376.6
XS GIS Cut Line= 4
2230965.91220532664153.231142395 2231288.9926563664210.128724705
2231337.59546275664214.3420461162231580.57458894664266.400028911
#Sta/Elev= 30
       0 2214.43    34.8 2215.65    55.1 2214.52   120.1 2198.67   150.4 2187.95
   160.8 2187.67   205.4 2176.95   221.6 2167.01   233.8 2162.46   274.4 2159.61
   294.7 2160.98   323.2 2160.75   332.6 2159.12   338.42156.215   343.3 2154.21
   351.3  2153.9   359.4 2154.08   368.52157.084   383.6 2163.69   391.7 2171.38
   399.9 2177.17   421.8 2184.78   461.3 2192.81   489.9 2205.84   510.4 2211.74
     539 2212.42   555.4 2214.54   575.8 2222.97   604.5 2231.88   625.3 2243.16
#Mann= 5, -1 ,  0
       0     0.1       0   338.4   0.045       0   368.5     0.1       0
  396.84    0.06       0  496.84     0.1       0
Bank Sta=338.4,368.5
XS Rating Curve= 0 ,0
Exp/Cntr(USF)=0,0
Exp/Cntr=0.3,0.1

Type RM Length L Ch R = 1 ,21504   ,333.9,336.6,337.3
XS GIS Cut Line= 2
2230828.33434328664450.5768442212231449.65372023664597.030697359
#Sta/Elev= 30
       0 2210.96    20.4 2209.17    86.1 2209.45   160.1 2188.34   172.4 2182.99
     193 2187.03   242.3 2160.79   275.2 2158.21   283.4 2150.24   287.5 2147.59
   291.4 2147.44   303.9  2147.7   313.5 2150.18   344.6 2152.99   357.4 2152.55
   365.6 2154.83   398.5 2152.74   410.8 2153.43     419 2157.41   443.7 2174.59
   451.9 2177.79     493 2184.97   530.8 2201.09   542.3  2204.7   554.6 2205.41
   567.4 2208.31   587.5 2209.37   600.7 2212.03   616.3 2217.25   638.3 2229.04
#Mann= 7, -1 ,  0
       0     0.1       0   283.4   0.045       0   313.5     0.1       0
     340    0.06       0     540    0.08       0     570     0.1       0
  638.35    0.08       0
Bank Sta=283.4,313.5
XS Rating Curve= 0 ,0
Exp/Cntr(USF)=0,0
Exp/Cntr=0.3,0.1

Type RM Length L Ch R = 1 ,21168   ,466.7,462.2,457
XS GIS Cut Line= 2
2230730.69844119664736.8275571732231345.36082481664940.975352457
#Sta/Elev= 30
       0  2219.6    26.8 2210.78    55.2 2204.08    94.3 2198.47   137.5 2194.49
   200.8  2171.9   229.5 2163.32   254.6 2158.25   267.1 2153.83   279.9 2157.15
   296.6 2152.92   314.7 2144.81  328.482142.916   338.7 2141.96     364  2142.9
   368.2 2143.89   415.9  2142.8   422.3  2145.6   435.7 2155.11   444.4 2159.55
   448.3 2161.02     461 2161.95   477.8 2169.19   503.1  2177.8   526.7 2184.66
     533 2184.67   553.7 2198.39   587.4 2210.65   625.4 2213.15   647.7 2218.53
#Mann= 5, -1 ,  0
       0     0.1       0  328.48   0.045       0     364     0.1       0
     440    0.06       0     550     0.1       0
Bank Sta=328.48,364
XS Rating Curve= 0 ,0
Exp/Cntr(USF)=0,0
Exp/Cntr=0.3,0.1

Type RM Length L Ch R = 1 ,20706   ,502.8,504.5,505.3
XS GIS Cut Line= 3
2230584.24458805665289.358003104 2231161.1840095665300.452991978
2231356.45581369665256.073036482
#Sta/Elev= 30
       0 2216.51    31.2  2212.1   103.9 2194.49     136 2191.41     196 2180.69
     240 2166.34     260 2158.37     288 2151.61     304 2144.22     316 2135.68
     352  2135.8     392 2133.79   396.2 2132.03   404.1 2129.66   419.8 2130.15
     428 2131.98     440 2135.42     456 2136.16     472  2140.7     476 2148.36
     480 2151.56     496 2152.27     512 2157.97     544 2163.19     564 2172.35
   580.1 2182.18   592.4 2187.51   686.8 2201.36   727.8 2211.54   777.3 2228.79
#Mann= 5, -1 ,  0
       0     0.1       0   396.2   0.045       0     428     0.1       0
     470    0.06       0     570     0.1       0
Bank Sta=396.2,428
XS Rating Curve= 0 ,0
Exp/Cntr(USF)=0,0
Exp/Cntr=0.3,0.1

Type RM Length L Ch R = 1 ,20201   ,605.1,608.6,605.8
XS GIS Cut Line= 3
2230504.36066815665755.3475358162231110.14706068 665770.88052024
2231329.82784039665704.310586996
#Sta/Elev= 30
       0 2219.17    35.8 2200.83    63.8 2190.42    91.8 2185.21   155.9 2184.51
   199.9 2179.24   251.9  2164.9   259.9 2160.75   271.9 2160.18   339.9 2140.57
   371.9 2135.06  390.922121.562   403.4 2118.93     416 2121.51   453.8    2124
     480  2121.5     500 2124.77   531.8 2124.66     540 2125.94   552.3 2133.13
     560 2135.07     568 2129.74     576 2129.41     592 2134.57     606 2135.93
     629 2147.62   670.8 2156.74     746 2183.14   771.1 2188.83   835.5 2196.54
#Mann= 6, -1 ,  0
       0    0.03       0      60     0.1       0  390.92   0.045       0
     416     0.1       0     450    0.06       0     550     0.1       0
Bank Sta=390.92,416
XS Rating Curve= 0 ,0
Exp/Cntr(USF)=0,0
Exp/Cntr=0.3,0.1

Type RM Length L Ch R = 1 ,19593   ,445.6,445.6,446.4
XS GIS Cut Line= 4
2230422.25775049666092.6351975892230750.66942116666310.096979522
2231201.12596945666334.5059550452231403.05476696666190.271099682
#Sta/Elev= 30
       0 2199.72    36.4 2195.35      97 2178.18   131.7 2178.64   169.2 2175.35
   195.2  2168.7   229.8 2154.52   275.8 2140.04   307.7 2137.43   333.3 2129.27
   348.7 2128.54   365.4 2123.21   427.4 2118.12   462.8 2110.72   471.5 2108.82
   491.5 2110.77   524.8  2113.9   684.5 2115.38   723.9 2119.31   735.9 2115.05
     804 2126.35   812.4 2131.96     828 2131.73     844 2127.96   859.6 2133.53
   922.5 2138.79    1003 2153.23  1045.4 2165.19  1060.3 2172.97  1093.2    2183
#Mann= 7, -1 ,  0
       0     0.1       0  403.88    0.07       0   462.8   0.045       0
   491.5    0.07       0  603.88     0.1       0  803.88    0.06       0
     905     0.1       0
Bank Sta=462.8,491.5
XS Rating Curve= 0 ,0
Exp/Cntr(USF)=0,0
Exp/Cntr=0.3,0.1

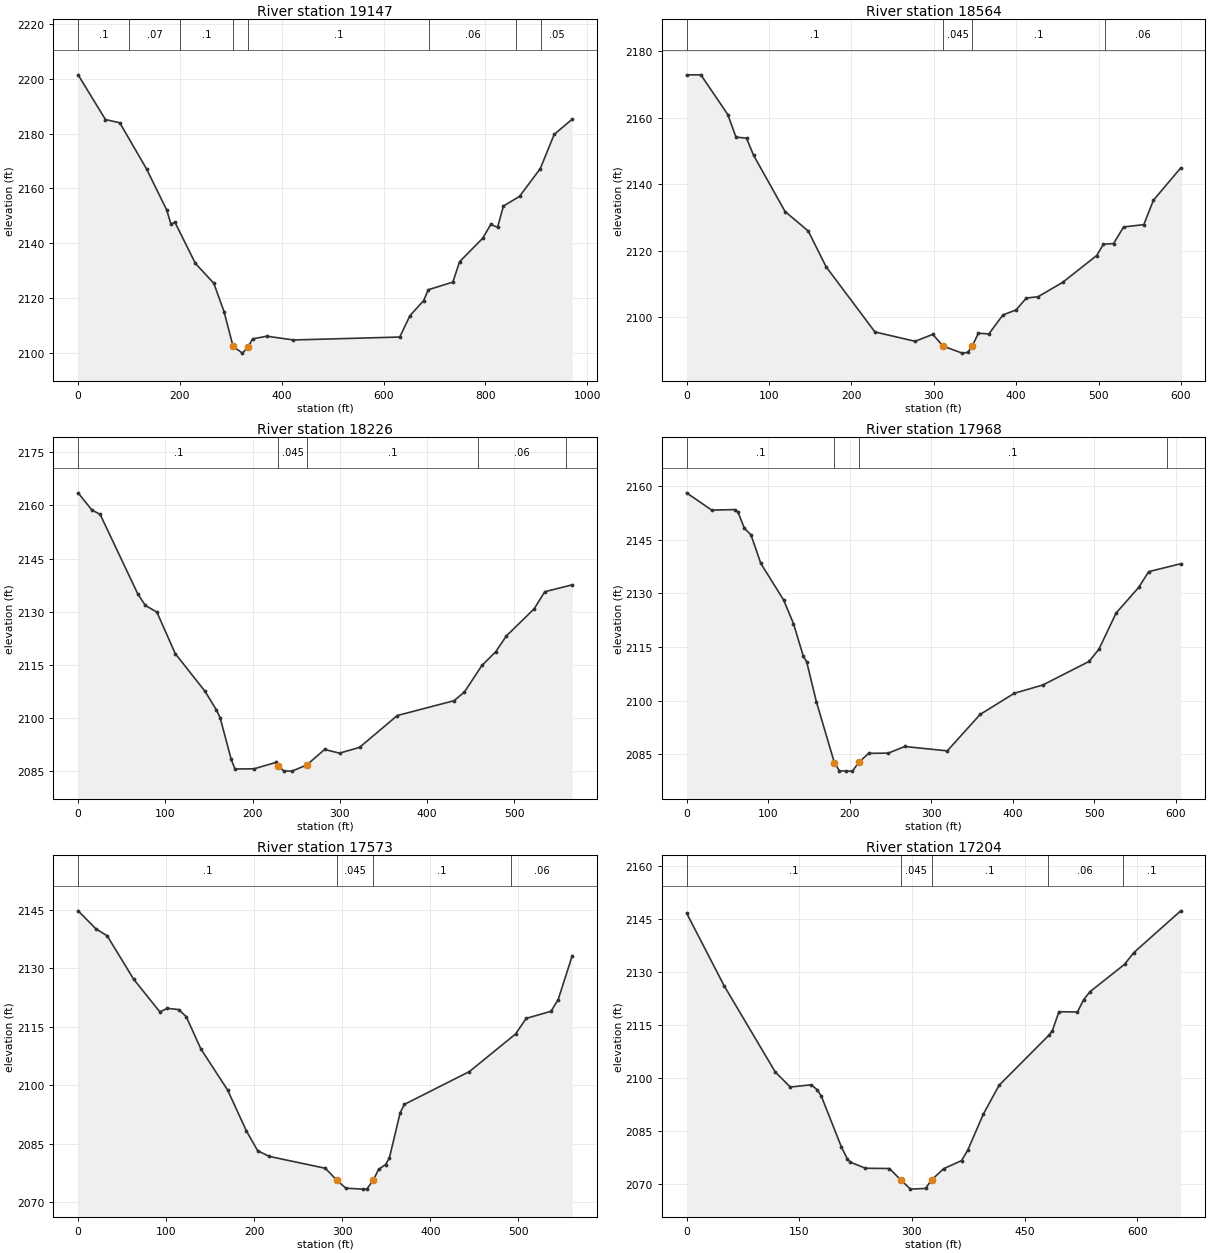
Type RM Length L Ch R = 1 ,19147   ,575.6,583.2,585.9
XS GIS Cut Line= 3
2230466.63770598666729.4875589632231203.34496722666791.619496658
2231407.49276251666900.350387625
#Sta/Elev= 30
       0 2201.45    53.7 2185.14    81.8 2183.96   134.4 2167.13   174.2 2152.09
   182.2 2147.03   190.2 2147.67   230.4 2132.66   266.5 2125.44   286.6  2115.1
  304.462102.378   322.7 2099.95   334.3 2102.31   342.7 2105.14   370.8 2106.12
     423 2104.75   631.8 2105.82   651.8 2113.61   678.6  2119.1     688 2123.08
   736.1 2125.86   749.3 2133.29   794.6 2141.82   810.7 2146.92   823.9 2145.84
   835.4 2153.59   867.2 2157.13   907.9 2167.28   935.1  2179.7   970.6 2185.27
#Mann= 8, -1 ,  0
       0     0.1       0     100    0.07       0     200     0.1       0
  304.46   0.045       0   334.3     0.1       0     690    0.06       0
  859.32     0.1       0  909.32    0.05       0
Bank Sta=304.46,334.3
XS Rating Curve= 0 ,0
Exp/Cntr(USF)=0,0
Exp/Cntr=0.3,0.1

Type RM Length L Ch R = 1 ,18564   ,336.3,337.4,336.8
XS GIS Cut Line= 3
2230479.95169263667219.8860671992230919.31325205667381.872904761
2231048.01512299667408.500878059
#Sta/Elev= 30
       0 2172.95    17.3 2172.95      50 2161.01    59.9 2154.22    72.7 2153.89
    81.2 2148.78   119.5 2131.83   147.6 2125.97   169.4 2115.17   228.6 2095.59
   277.3 2092.78   298.7 2094.86   311.5 2091.31   334.5 2089.22   341.3 2089.45
  346.742091.362   354.1  2095.2   366.9 2095.01   383.9 2100.71   399.9 2102.22
   412.3 2105.78   426.6 2106.19   456.4 2110.51   497.7 2118.58   505.9 2121.99
   518.2 2122.18   530.4 2127.18   554.9 2127.88   566.6 2135.23   599.7 2144.95
#Mann= 4, -1 ,  0
       0     0.1       0   311.5   0.045       0  346.74     0.1       0
  508.27    0.06       0
Bank Sta=311.5,346.74
XS Rating Curve= 0 ,0
Exp/Cntr(USF)=0,0
Exp/Cntr=0.3,0.1

Type RM Length L Ch R = 1 ,18226   ,262.5,258.3,254
XS GIS Cut Line= 3
2230420.03875271667552.7357334222230746.23142561667676.999608812
2230963.69320754667668.123617713
#Sta/Elev= 30
       0 2163.51    15.9 2158.62    25.2 2157.47    68.6 2134.94    77.2 2131.77
    90.3 2129.91   111.4 2118.21   145.7 2107.54   158.5 2102.37   162.8  2100.2
   175.6 2088.39   179.9  2085.7   201.9 2085.76   226.7 2087.54   229.8 2086.68
   235.6 2085.16   245.3  2085.1   262.2 2086.83   282.7 2091.21   299.8 2090.16
   322.8  2091.8   366.1 2100.77   431.1 2104.94   443.1  2107.4   463.1 2114.87
   479.1 2118.78   491.1 2123.17   523.1 2130.85   535.2 2135.65   566.7 2137.59
#Mann= 5, -1 ,  0
       0     0.1       0   229.8   0.045       0   262.2     0.1       0
  459.06    0.06       0  559.06     0.1       0
Bank Sta=229.8,262.2
XS Rating Curve= 0 ,0
Exp/Cntr(USF)=0,0
Exp/Cntr=0.3,0.1

Type RM Length L Ch R = 1 ,17968   ,400.3,394.8,389.7
XS GIS Cut Line= 3
2230377.53354688667867.7961876282230765.85815747 667901.08115425
2230978.88194386667863.358192078
#Sta/Elev= 30
       0  2158.1    30.8 2153.26    58.9 2153.41    62.9 2152.78    70.9 2148.17
    78.9 2146.38      91 2138.37   119.1 2128.09   131.1 2121.52   143.2 2112.37
   147.2  2110.9   159.2 2099.67   181.2 2082.66   187.3 2080.38   195.4 2080.25
   203.4 2080.25   211.62082.837   223.5 2085.22   247.5 2085.29   267.6 2087.14
   319.8 2085.92     360  2096.1     402 2102.04   436.8 2104.33   493.7 2110.93
   505.8 2114.37   526.8 2124.45   554.6 2131.66   566.8 2136.05   606.1 2138.26
#Mann= 4, -1 ,  0
       0     0.1       0   181.2   0.045       0   211.6     0.1       0
  589.75    0.06       0
Bank Sta=181.2,211.6
XS Rating Curve= 0 ,0
Exp/Cntr(USF)=0,0
Exp/Cntr=0.3,0.1

Type RM Length L Ch R = 1 ,17573   ,361,368.9,375.9
XS GIS Cut Line= 3
2230493.26567928668313.8519701862230859.40031213668176.274108147
2231028.04414301668154.084130399
#Sta/Elev= 30
       0 2144.72    20.2 2140.11      33 2138.32    62.9 2127.25    92.8 2118.81
   101.4 2119.73   114.2  2119.4   122.8 2117.58   139.4 2109.32   169.8 2098.77
   191.1  2088.3   203.9 2083.22   217.1 2081.75   280.9  2078.7   293.7 2075.67
   304.1  2073.6   323.6 2073.36   327.9 2073.38   335.1 2075.63   341.3 2078.43
   349.2 2079.67   353.5 2081.33   365.8 2092.96   370.6 2095.09   444.5 2103.52
   496.8 2113.13   508.9 2117.14   537.2 2118.97   545.2 2121.95   561.2  2133.2
#Mann= 4, -1 ,  0
       0     0.1       0   293.7   0.045       0   335.1     0.1       0
  491.13    0.06       0
Bank Sta=293.7,335.1
XS Rating Curve= 0 ,0
Exp/Cntr(USF)=0,0
Exp/Cntr=0.3,0.1

Type RM Length L Ch R = 1 ,17204   ,248.9,251.5,255.1
XS GIS Cut Line= 3
2230482.17069041668566.817716516 2230852.7433188668569.036714291
2231127.89904288668651.139631959
#Sta/Elev= 30
       0 2146.77      50 2126.16     118 2101.74     138 2097.47     166 2098.11
     174 2096.66   179.3  2094.9     206 2080.52     214 2077.06     218 2076.17
     238 2074.45     270 2074.37   285.4 2071.07     298 2068.53     318 2068.73
     326 2071.11     342 2074.31     366 2076.62   374.2 2079.56     395  2089.8
   415.9 2097.96   482.8 2112.28   486.9 2113.46   495.6 2118.81   520.3 2118.75
   528.6 2122.28     537  2124.5   582.9 2132.24   595.3 2135.58   657.7 2147.42
#Mann= 5, -1 ,  0
       0     0.1       0   285.4   0.045       0     326     0.1       0
  480.58    0.06       0  580.58     0.1       0
Bank Sta=285.4,326
XS Rating Curve= 0 ,0
Exp/Cntr(USF)=0,0
Exp/Cntr=0.3,0.1

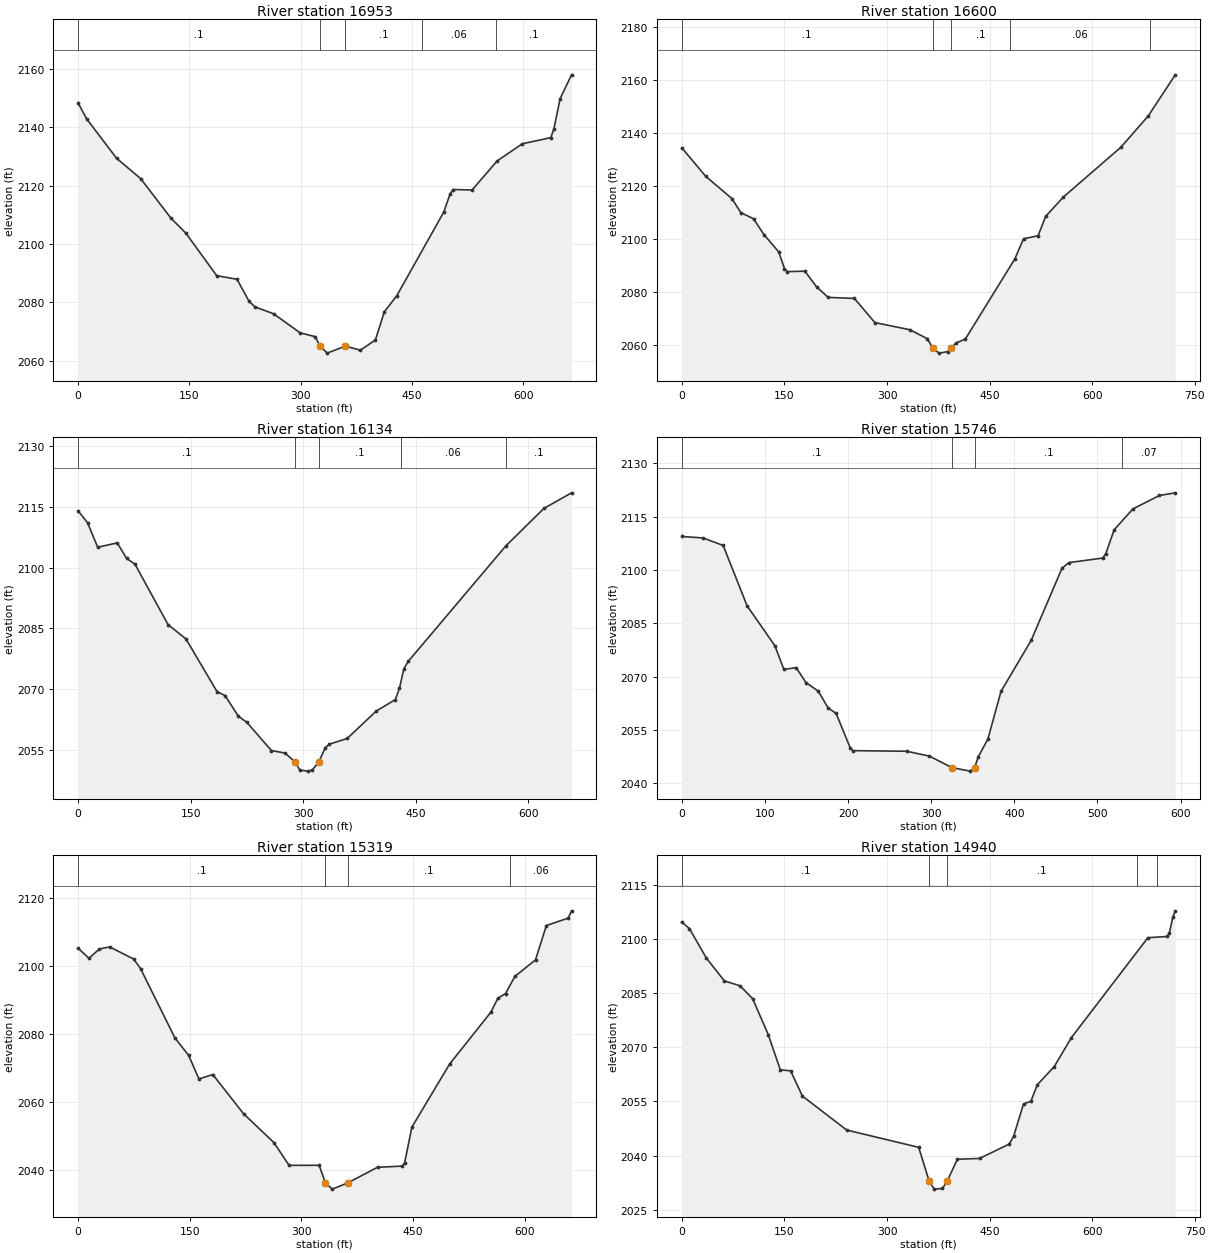
Type RM Length L Ch R = 1 ,16953   ,351,353.3,356.6
XS GIS Cut Line= 3
2230408.94376384668757.651525151 2230826.1153455 668826.44045617
2231054.67211631668906.324376064
#Sta/Elev= 30
       0 2148.28    11.4 2142.86    51.9 2129.31    84.4 2122.34   124.9 2108.89
   145.2  2103.7   186.8 2089.14   214.1 2087.92   230.3 2080.41   238.4 2078.44
   263.4 2076.11   299.2 2069.57   319.5 2068.27     3262065.048   335.7 2062.63
     360 2065.04   380.3 2063.64   400.6 2067.11   412.7 2076.79   429.2 2082.17
   492.8 2110.93   501.3 2117.15   505.5 2118.63   530.9 2118.46   564.7 2128.42
   598.7 2134.29   636.9 2136.38   641.1  2139.3   649.5 2149.69   664.9 2157.88
#Mann= 5, -1 ,  0
       0     0.1       0     326   0.045       0     360     0.1       0
   462.8    0.06       0   562.8     0.1       0
Bank Sta=326,360
XS Rating Curve= 0 ,0
Exp/Cntr(USF)=0,0
Exp/Cntr=0.3,0.1

Type RM Length L Ch R = 1 ,16600   ,459.9,465.9,472.9
XS GIS Cut Line= 3
2230311.30786175 669019.493262582230812.80135886 669203.67007789
2230999.19717194669188.137093466
#Sta/Elev= 30
       0 2134.41      35 2123.62    73.4 2115.19    86.1 2109.94   104.8 2107.58
   120.2 2101.55   141.5 2095.11   150.1 2088.76   154.3 2087.58   179.9 2087.76
   196.9 2081.85     214 2077.83   252.3 2077.45   282.2 2068.31   333.3  2065.6
   358.9 2062.22   366.6 2058.77   375.9 2056.75   388.5  2057.3   393.82058.707
   400.9 2060.62   414.3 2062.02   486.7 2092.33   499.5    2100   520.8 2101.16
   531.8 2108.45   557.7 2115.78     642 2134.68   682.1 2146.57   721.3 2162.03
#Mann= 5, -1 ,  0
       0     0.1       0   366.6   0.045       0   393.8     0.1       0
     480    0.06       0  684.24     0.1       0
Bank Sta=366.6,393.8
XS Rating Curve= 0 ,0
Exp/Cntr(USF)=0,0
Exp/Cntr=0.3,0.1

Type RM Length L Ch R = 1 ,16134   ,383.9,388.1,391.5
XS GIS Cut Line= 2
2230169.29200416669290.2109911082230621.96755022669767.295512695
#Sta/Elev= 30
       0 2114.04    12.6 2111.12    26.1 2105.03    52.2 2106.11    64.7 2102.28
    75.8 2100.86   119.9  2085.9   143.7 2082.38   185.2 2069.33     196 2068.35
   213.6 2063.24   224.7 2061.79   257.7 2054.76   275.8 2054.14   288.9    2052
   295.6 2049.93   306.4 2049.67   312.2 2049.95     321 2052.03   329.6 2055.49
   334.9 2056.33   358.7 2057.75   397.4 2064.52   422.9 2067.37   428.4 2070.21
   434.2 2074.95     440  2076.8     570 2105.34   620.9 2114.63   657.7 2118.49
#Mann= 5, -1 ,  0
       0     0.1       0   288.9   0.045       0     321     0.1       0
     430    0.06       0     570     0.1       0
Bank Sta=288.9,321
XS Rating Curve= 0 ,0
Exp/Cntr(USF)=0,0
Exp/Cntr=0.3,0.1

Type RM Length L Ch R = 1 ,15746   ,428.3,427.2,426.9
XS GIS Cut Line= 2
2229920.76425338669454.416826445  2230200.357973669978.100301303
#Sta/Elev= 30
       0 2109.44    25.3 2109.02    49.7 2106.93    78.5 2089.96     112  2078.7
   122.8 2072.03   137.6 2072.56   149.4 2068.34   164.2 2065.93     176 2061.21
   185.6 2059.69   202.6    2050   205.6 2049.21   270.5 2049.04   297.9 2047.67
   325.1 2044.42     347 2043.45   352.3 2044.45   356.8 2047.54   368.2 2052.47
     384 2065.88   420.3 2080.23   457.4 2100.53   465.6 2102.08   506.4 2103.37
   510.1 2104.64   520.1 2111.32   542.7 2117.19   574.5 2120.96   593.6 2121.71
#Mann= 4, -1 ,  0
       0     0.1       0   325.1   0.045       0   352.3     0.1       0
     530    0.07       0
Bank Sta=325.1,352.3
XS Rating Curve= 0 ,0
Exp/Cntr(USF)=0,0
Exp/Cntr=0.3,0.1

Type RM Length L Ch R = 1 ,15319   ,378.5,378.7,378.9
XS GIS Cut Line= 2
2229505.81166949669596.4326840332229836.44233793670171.153107712
#Sta/Elev= 30
       0 2105.28    14.7 2102.31    28.5 2105.05    42.4 2105.67    74.7  2102.1
    83.9  2099.3   130.1 2078.91   148.5  2073.8   162.4 2066.86     181 2068.16
   222.4 2056.62     263 2048.18   283.5 2041.47   323.9 2041.48   332.4 2036.29
   341.6 2034.48   362.6 2036.34   402.3  2040.9   435.8 2041.25   438.8 2042.26
   448.5  2052.7   499.2 2071.24   554.6 2086.47   563.9 2090.53   574.3 2091.97
   586.9 2096.99   614.6 2101.86   629.2 2111.95   658.5 2114.12     663 2116.27
#Mann= 4, -1 ,  0
       0     0.1       0   332.4   0.045       0   362.6     0.1       0
     580    0.06       0
Bank Sta=332.4,362.6
XS Rating Curve= 0 ,0
Exp/Cntr(USF)=0,0
Exp/Cntr=0.3,0.1

Type RM Length L Ch R = 1 ,14940   ,421.8,413.5,408.7
XS GIS Cut Line= 3
2229170.74300549669762.8575171452229397.08077852670168.934109938
2229599.00957603 670326.48295195
#Sta/Elev= 30
       0 2104.74    11.2 2102.91    35.8 2094.77    62.2 2088.41    85.1 2087.06
   103.4 2083.51   126.3 2073.54   143.9 2063.77     159 2063.48   176.2 2056.49
   240.9 2047.07   346.1 2042.28   361.5 2032.85     369 2030.69   380.9 2030.87
  387.742032.926   402.7 2038.98     435 2039.19   478.3 2043.17   484.8 2045.32
   499.3 2054.32     510 2055.03   519.6 2059.65   544.2 2064.67   569.3  2072.7
     681 2100.39   709.5 2100.73   712.4 2101.66   717.4 2106.11     721 2107.84
#Mann= 5, -1 ,  0
       0     0.1       0   361.5   0.045       0  387.74     0.1       0
  664.89    0.06       0  694.89     0.1       0
Bank Sta=361.5,387.74
XS Rating Curve= 0 ,0
Exp/Cntr(USF)=0,0
Exp/Cntr=0.3,0.1

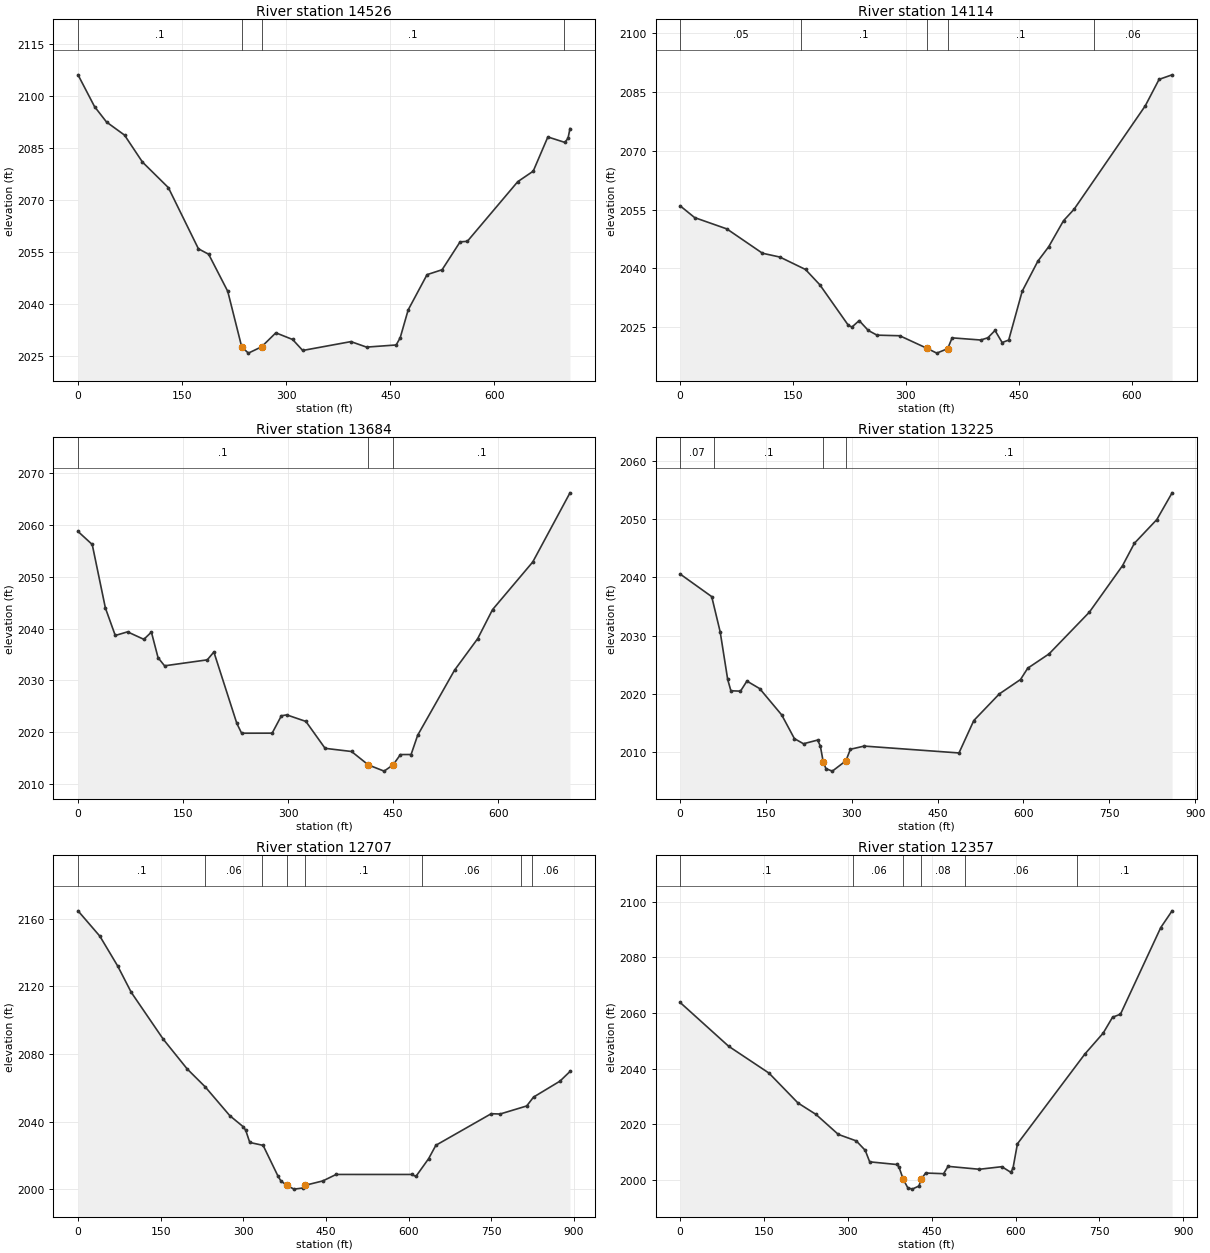
Type RM Length L Ch R = 1 ,14526   ,413.1,412.4,412
XS GIS Cut Line= 2
2228804.60837264670155.6201232892229390.42378519670555.039722757
#Sta/Elev= 30
       0 2106.21    23.8 2097.03    41.1 2092.56      67 2088.79    92.9 2080.98
   130.2  2073.6   173.5 2055.92   188.3 2054.33   215.8 2043.61   235.9 2027.56
   245.5 2025.75  264.512027.571   285.1 2031.62   309.3 2029.69   323.8 2026.52
   393.3 2029.08   415.8 2027.49   458.5 2028.11   464.3 2030.19   475.8 2038.25
     503 2048.44   524.7 2049.86   550.6 2057.91   561.1 2058.08   633.7 2075.32
     656 2078.36   677.1 2088.25   701.5 2086.68   706.1 2087.84     709 2090.67
#Mann= 4, -1 ,  0
       0     0.1       0   235.9   0.045       0  264.51     0.1       0
     700    0.06       0
Bank Sta=235.9,264.51
XS Rating Curve= 0 ,0
Exp/Cntr(USF)=0,0
Exp/Cntr=0.3,0.1

Type RM Length L Ch R = 1 ,14114   ,418.5,430.3,434.3
XS GIS Cut Line= 2
2228655.93552173670486.2507917372229206.24696988670839.071437934
#Sta/Elev= 30
       0 2055.98    19.3 2052.97    62.1 2050.08   109.4 2043.87   132.6 2042.89
   166.6 2039.72   185.6 2035.82   223.6 2025.44   228.4 2025.03   237.9 2026.67
     250 2024.15   261.6 2022.95   291.8  2022.8   328.1 2019.58     341 2018.36
   355.5  2019.5   361.4 2022.26   399.4 2021.71   408.9 2022.28   418.4 2024.15
   427.9 2021.06   436.6  2021.7   454.5 2034.16   475.4 2041.87   489.7 2045.52
   509.4 2052.17   523.4 2055.09     618  2081.5   636.4 2088.27   653.7 2089.43
#Mann= 5, -1 ,  0
       0    0.05       0     160     0.1       0   328.1   0.045       0
   355.5     0.1       0     550    0.06       0
Bank Sta=328.1,355.5
XS Rating Curve= 0 ,0
Exp/Cntr(USF)=0,0
Exp/Cntr=0.3,0.1

Type RM Length L Ch R = 1 ,13684   ,458,458.9,454.6
XS GIS Cut Line= 3
2228436.25474202670603.857673803 2228693.6584839671023.248253244
2228884.49229254671112.008164237
#Sta/Elev= 30
       0 2058.69    20.3 2056.18    39.1 2043.95    53.2 2038.66    70.7 2039.36
      94 2037.92   104.8 2039.31   114.3 2034.38   123.6 2032.82   184.6 2033.97
     194 2035.48   226.8 2021.72   233.6 2019.84   277.2 2019.85   290.4  2023.2
   298.1 2023.37   325.4 2022.11   352.8 2016.93   390.6 2016.32   414.6 2013.73
   437.1 2012.54  449.96 2013.76   460.4 2015.73   475.6 2015.74     485 2019.45
   537.6 2031.97   570.7 2038.05   591.9 2043.64   649.3 2052.81   702.5 2066.13
#Mann= 3, -1 ,  0
       0     0.1       0   414.6   0.045       0  449.96     0.1       0
Bank Sta=414.6,449.96
XS Rating Curve= 0 ,0
Exp/Cntr(USF)=0,0
Exp/Cntr=0.3,0.1

Type RM Length L Ch R = 1 ,13225   ,537.5,517.5,495
XS GIS Cut Line= 4
2228060.66618149670941.7136801262228209.47639743671086.935119632
2228273.82904472671177.6237002452228795.73238154671318.374957295
#Sta/Elev= 30
       0 2040.57    55.2 2036.69      70 2030.64    83.1 2022.48    88.7 2020.53
   105.5 2020.46   116.7 2022.19     139  2020.9   177.5 2016.38   199.7 2012.31
   215.6 2011.43   240.2 2012.06     245 2011.05   250.12008.302   254.8 2007.15
     266 2006.73   289.72008.506   297.5 2010.48   321.6 2011.03   487.3 2009.85
   513.2 2015.42   557.7 2019.98   594.8 2022.46   607.4  2024.4   644.7 2026.86
   715.1 2034.02   773.1 2042.01   793.8 2045.85     833 2049.92   859.7 2054.51
#Mann= 4, -1 ,  0
       0    0.07       0      60     0.1       0   250.1   0.045       0
   289.7     0.1       0
Bank Sta=250.1,289.7
XS Rating Curve= 0 ,0
Exp/Cntr(USF)=0,0
Exp/Cntr=0.3,0.1

Type RM Length L Ch R = 1 ,12707   ,348.2,350.7,353.1
BEGIN DESCRIPTION:
Structure XS 4
END DESCRIPTION:
XS GIS Cut Line= 3
2227877.06730277671564.6837103012228176.63200237671617.939656896
2228762.44741492671558.026716976
#Sta/Elev= 30
       0 2164.59    39.7 2149.58    72.2 2131.86    96.6 2116.42   154.9 2088.63
   198.2 2071.11   230.8 2060.56   275.6 2043.48   299.7 2037.01   304.3 2034.97
   311.8 2027.66     336 2025.94   362.9 2007.85   368.1 2004.99     379 2002.26
   392.1 2000.07   408.3 2000.73   412.4 2002.34   444.5 2004.93   468.6 2008.75
   605.4 2008.74   613.4 2007.59   636.5 2018.09   649.6 2025.99   750.1 2044.65
   766.2 2044.47   814.5 2049.23   826.9 2054.47   874.8 2063.89   893.1 2069.61
#Mann= 8, -1 ,  0
       0     0.1       0     230    0.06       0  334.26     0.1       0
     379   0.045       0   412.4     0.1       0  624.26    0.06       0
  804.26     0.1       0  824.26    0.06       0
Bank Sta=379,412.4
XS Rating Curve= 0 ,0
Exp/Cntr(USF)=0,0
Exp/Cntr=0.3,0.1

Type RM Length L Ch R = 1 ,12357   ,103.1,103.8,104.3
BEGIN DESCRIPTION:
Structure XS 3
END DESCRIPTION:
XS GIS Cut Line= 2
2227889.52349233671935.6893554752228768.44632096671980.624060415
#Sta/Elev= 30
       0  2063.8    86.8 2048.03   158.9 2038.37   210.9 2027.59     243 2023.49
     283 2016.28   315.1 2013.95   331.1 2010.56   339.1 2006.41   387.2 2005.45
   391.2 2004.71   399.2 2000.09   407.2 1997.08   415.2 1996.58   427.2  1997.7
   431.2 2000.15   439.2 2002.38   471.3 2002.14   479.3 2004.78   535.3 2003.73
   575.5 2004.66   591.4 2002.66   595.4 2004.03   603.4  2012.9   724.1 2045.24
   756.8 2052.76   773.6 2058.49   787.7 2059.56   859.8 2090.76   880.1 2096.79
#Mann= 6, -1 ,  0
       0     0.1       0     310    0.06       0   399.2   0.045       0
   431.2    0.08       0     510    0.06       0     710     0.1       0
Bank Sta=399.2,431.2
XS Rating Curve= 0 ,0
Exp/Cntr(USF)=0,0
Exp/Cntr=0.3,0.1

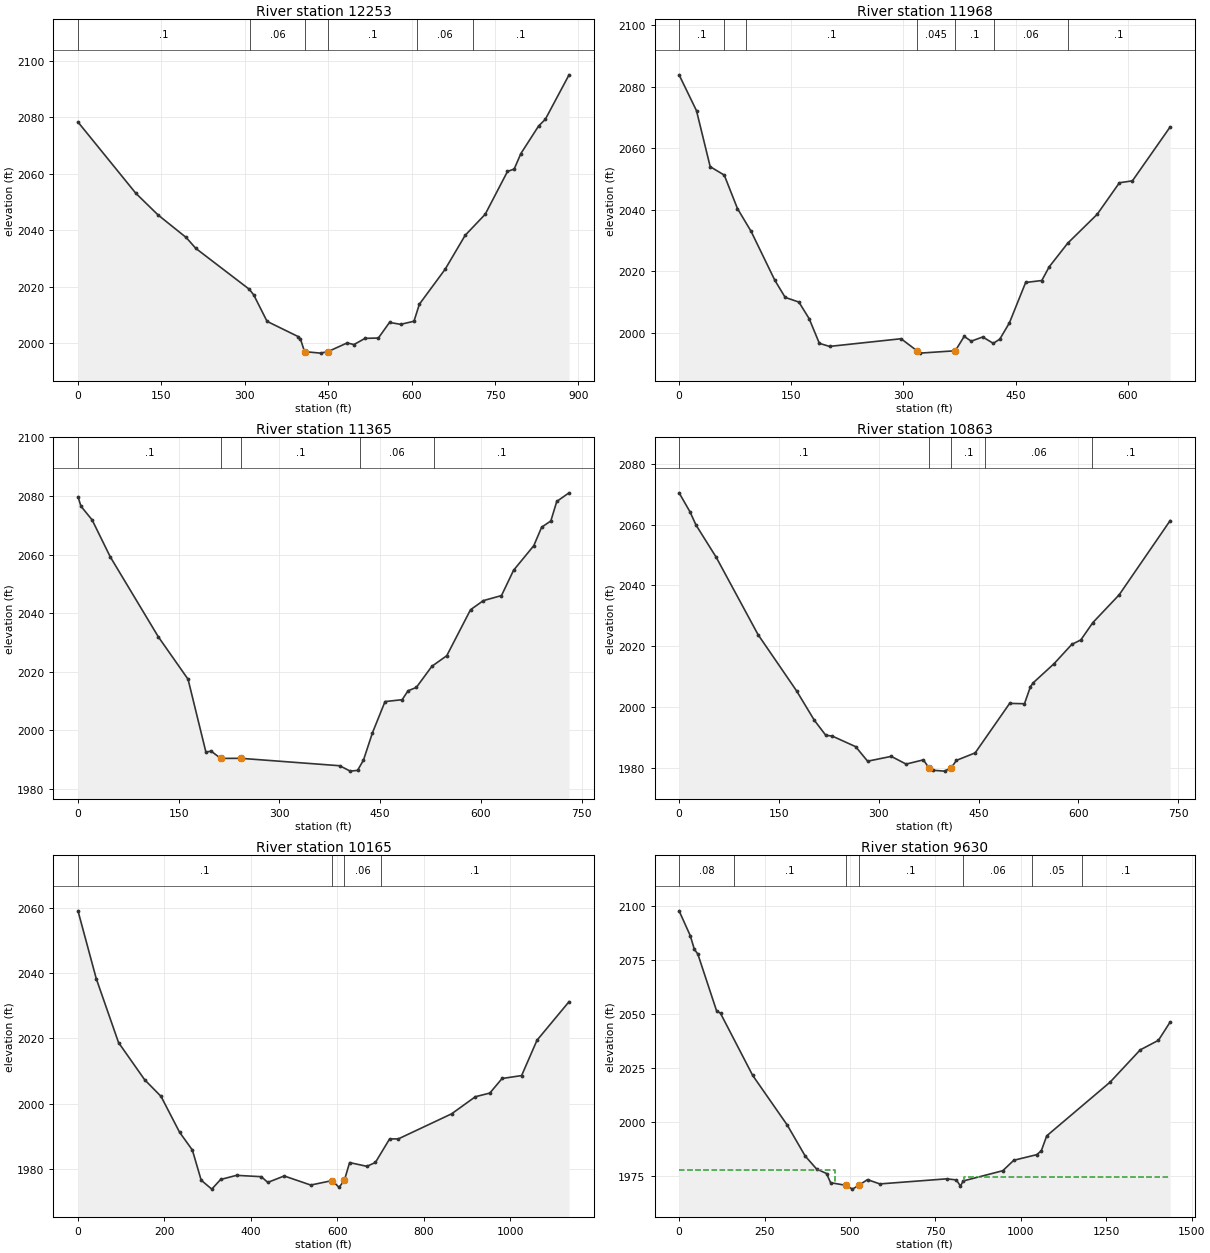
Type RM Length L Ch R = 1 ,12253   ,292.6,285,278.8
BEGIN DESCRIPTION:
Structure XS 2
END DESCRIPTION:
XS GIS Cut Line= 2
2227888.28724873672043.1338068912228770.80485376672077.284182645
#Sta/Elev= 30
       0 2078.33     104 2053.09     144  2045.4   194.6  2037.4     212 2033.53
   308.1 2019.05   316.1 2017.05   340.1 2007.67   396.2 2002.26   400.2 2001.34
  407.561996.941   436.2 1996.41   449.91996.975   484.2 2000.03   496.3 1999.44
   516.3 2001.64   540.3 2001.77   560.3 2007.29   580.3 2006.62   604.3 2007.71
     614 2013.75   660.4 2026.16   696.4 2038.18   732.4 2045.63   772.5 2060.82
   784.5 2061.65   796.5 2067.13   828.5 2076.94   840.5 2079.28   883.2 2095.06
#Mann= 6, -1 ,  0
       0     0.1       0     310    0.06       0  407.56   0.045       0
   449.9     0.1       0     610    0.06       0     710     0.1       0
Bank Sta=407.56,449.9
XS Rating Curve= 0 ,0
Exp/Cntr(USF)=0,0
Exp/Cntr=0.3,0.1

Type RM Length L Ch R = 1 ,11968   ,602.2,602.4,603
BEGIN DESCRIPTION:
Structure XS 1
END DESCRIPTION:
XS GIS Cut Line= 4
 2228123.7444521 672478.820528632228382.48002948672336.851496618
2228463.54172283 672309.830932172228718.87156887672204.512033031
#Sta/Elev= 30
       0 2083.81    23.3 2072.16    41.6 2054.01    60.4 2051.28    78.1  2040.4
    96.3 2033.02   128.1 2017.13   141.9 2011.59   160.2 2010.08   173.9 2004.72
   187.6 1996.69   201.2 1995.69   296.9 1998.18     318 1994.31   322.2 1993.51
  369.49 1994.28   381.3 1998.94   390.7 1997.39   406.1 1998.75   420.2 1996.69
   428.9 1998.03   441.8 2003.34   463.5 2016.43   485.1 2017.07   494.9 2021.47
   519.7 2029.16   559.2 2038.56   588.9 2048.79   606.3 2049.41   656.8 2066.91
#Mann= 7, -1 ,  0
       0     0.1       0      60    0.06       0      90     0.1       0
     318   0.045       0  369.49     0.1       0  420.57    0.06       0
  520.57     0.1       0
Bank Sta=318,369.49
XS Rating Curve= 0 ,0
Exp/Cntr(USF)=0,0
Exp/Cntr=0.3,0.1

Type RM Length L Ch R = 1 ,11365   ,502.2,502.6,503.6
XS GIS Cut Line= 2
2228316.11676972673005.2228055962228976.64148458672691.701857988
#Sta/Elev= 30
       0 2079.75     4.5 2076.52    21.1 2071.84    48.1 2059.24   119.6 2031.97
   163.9 2017.48   190.5  1992.6   198.2 1992.94   212.6 1990.45   242.6 1990.48
   389.7 1987.95   405.4 1986.11   416.3 1986.37   425.1 1989.86   438.4 1999.15
   457.2 2009.85   482.7 2010.49   491.5 2013.54   503.8 2014.67     527  2021.9
   549.1  2025.5   584.5  2041.2   603.6 2044.31   630.6 2046.03   648.6 2054.67
   678.7 2063.06   690.4 2069.37   704.1  2071.5   712.9 2078.16   731.2  2081.1
#Mann= 5, -1 ,  0
       0     0.1       0   212.6   0.045       0   242.6     0.1       0
     420    0.06       0     530     0.1       0
Bank Sta=212.6,242.6
XS Rating Curve= 0 ,0
Exp/Cntr(USF)=0,0
Exp/Cntr=0.3,0.1

Type RM Length L Ch R = 1 ,10863   ,686.1,698.1,705
XS GIS Cut Line= 2
2228477.44308256673413.1044267572229141.01169012673090.451801063
#Sta/Elev= 30
       0 2070.51    16.4 2064.25    25.3 2059.95    55.9 2049.24   118.7 2023.79
   176.5  2005.3   203.2 1995.61   220.5 1990.63   229.9 1990.42   265.3 1986.91
   283.3 1982.12   318.8 1983.71   341.1 1981.17   367.1 1982.56  375.161979.997
   381.1 1979.14   398.9 1978.85     409 1979.96   416.7 1982.39   444.9 1984.86
   496.7 2001.16     519 2001.05   527.9 2006.65   532.3 2007.98   563.5 2014.25
   590.1  2020.6   603.6 2022.05   621.8 2027.79   661.3 2036.93   737.9 2061.37
#Mann= 5, -1 ,  0
       0     0.1       0  375.16   0.045       0     409     0.1       0
     460    0.06       0     620     0.1       0
Bank Sta=375.16,409
XS Rating Curve= 0 ,0
Exp/Cntr(USF)=0,0
Exp/Cntr=0.3,0.1

Type RM Length L Ch R = 1 ,10165   ,534.1,535.1,520.6
XS GIS Cut Line= 4
2228512.30904705673710.6281963062228757.18063123673802.079644755
2229199.31075814673894.3612120612229578.75937763673708.631098308
#Sta/Elev= 30
       0 2059.08    42.3 2038.31    93.8 2018.74   154.2 2007.35     192 2002.27
     235 1991.27   264.5 1985.83   284.9 1976.59   309.4 1973.86   329.8 1976.81
   366.6 1978.08   423.8 1977.67     439 1975.92   476.9 1977.89   538.2 1975.11
   588.21976.489   603.6 1974.39   615.91976.528   628.1 1981.99   668.1 1980.84
   687.7 1982.02   720.6 1989.24   740.7 1989.24   864.1 1996.93   918.9 2002.16
   952.3 2003.27   980.7 2007.74  1025.8 2008.63  1061.4 2019.45  1135.5 2031.26
#Mann= 4, -1 ,  0
       0     0.1       0   588.2   0.045       0   615.9    0.06       0
  701.39     0.1       0
Bank Sta=588.2,615.9
XS Rating Curve= 0 ,0
Exp/Cntr(USF)=0,0
Exp/Cntr=0.3,0.1

Type RM Length L Ch R = 1 ,9630    ,556.7,559,552.1
XS GIS Cut Line= 4
2228320.91169151674409.9741852972228638.45027309674198.281797579
2229315.46649419674192.2905035872229676.94123171674304.127991438
#Sta/Elev= 30
       0 2097.77    32.8 2086.24    44.7 2079.92    54.8 2077.78   109.6 2051.52
   121.2 2050.32   215.4 2021.56   316.4  1998.6   369.2  1984.2   402.4 1978.23
   431.4 1976.14   443.4 1971.89   488.11970.671   507.4 1968.91  525.53 1970.67
   551.4 1973.31   587.4 1971.32   783.4 1973.68   811.4 1973.17   823.4 1970.34
   831.4 1972.69   947.3 1977.44   979.4 1982.27  1046.6 1984.87    1060 1986.64
  1075.9 1993.59  1261.4 2018.46  1349.4 2033.38  1402.8 2037.82  1437.1  2046.3
#Mann= 7, -1 ,  0
       0    0.08       0     160     0.1       0   488.1   0.045       0
  525.53     0.1       0  831.63    0.06       0 1031.63    0.05       0
 1178.68     0.1       0
#XS Ineff= 2 , 0
          455.07 1977.66  834.99         1974.73
Permanent Ineff=
       F       F
Bank Sta=488.1,525.53
XS Rating Curve= 0 ,0
Exp/Cntr(USF)=0,0
Exp/Cntr=0.3,0.1