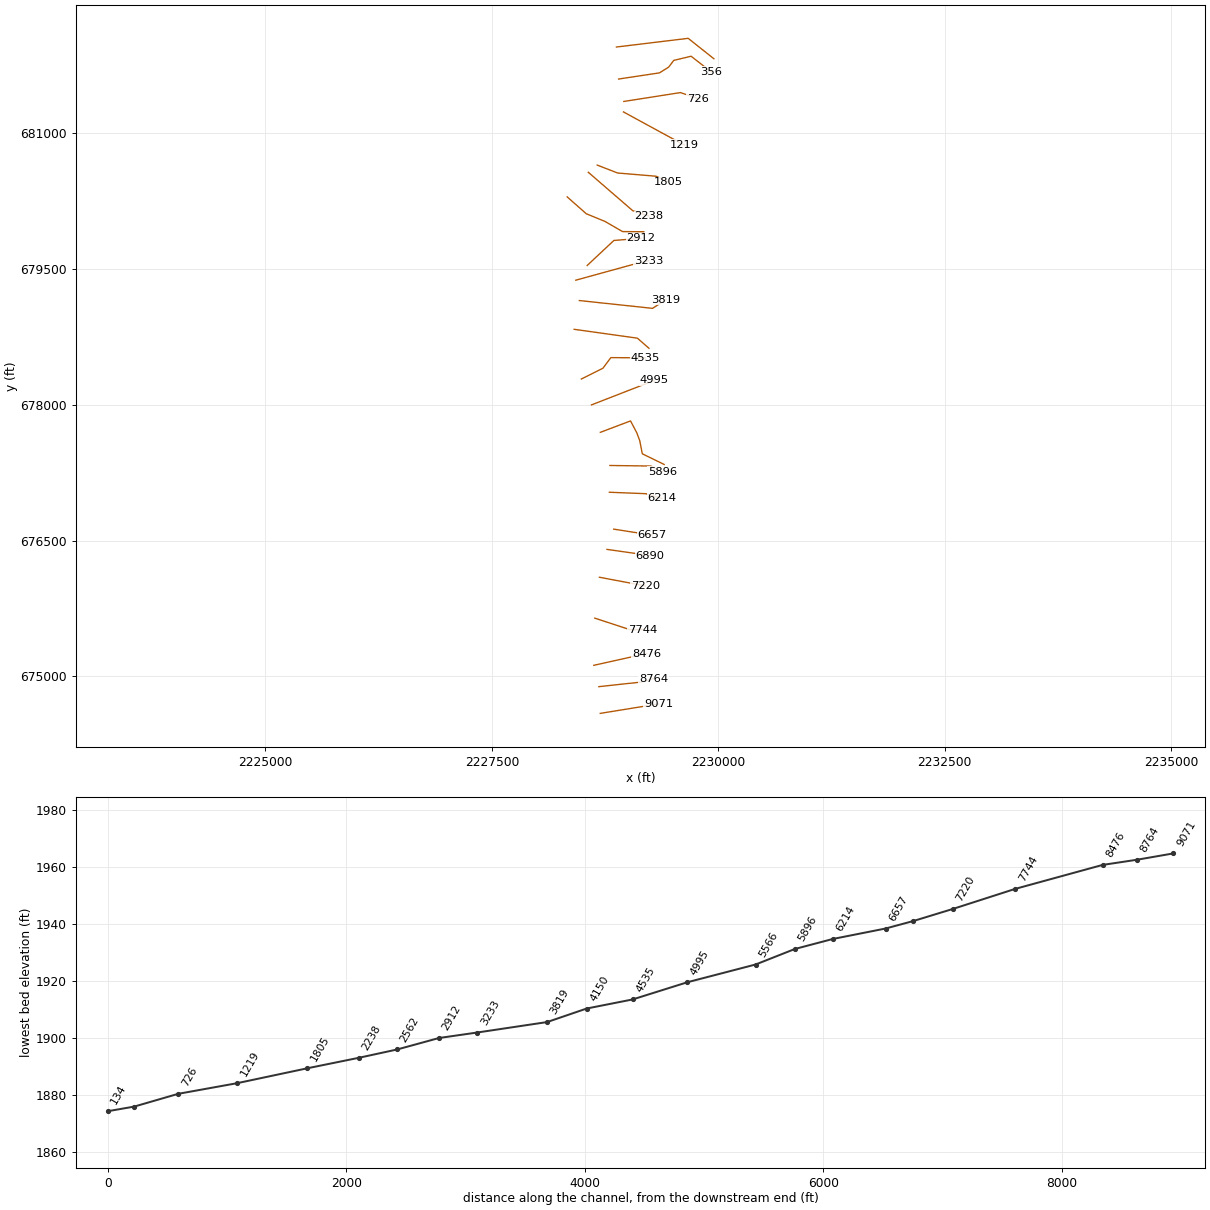
HEC-RAS study LONGRN.prj: LONGRN

--- LONGRN.g01 (geometry) --- (continued)

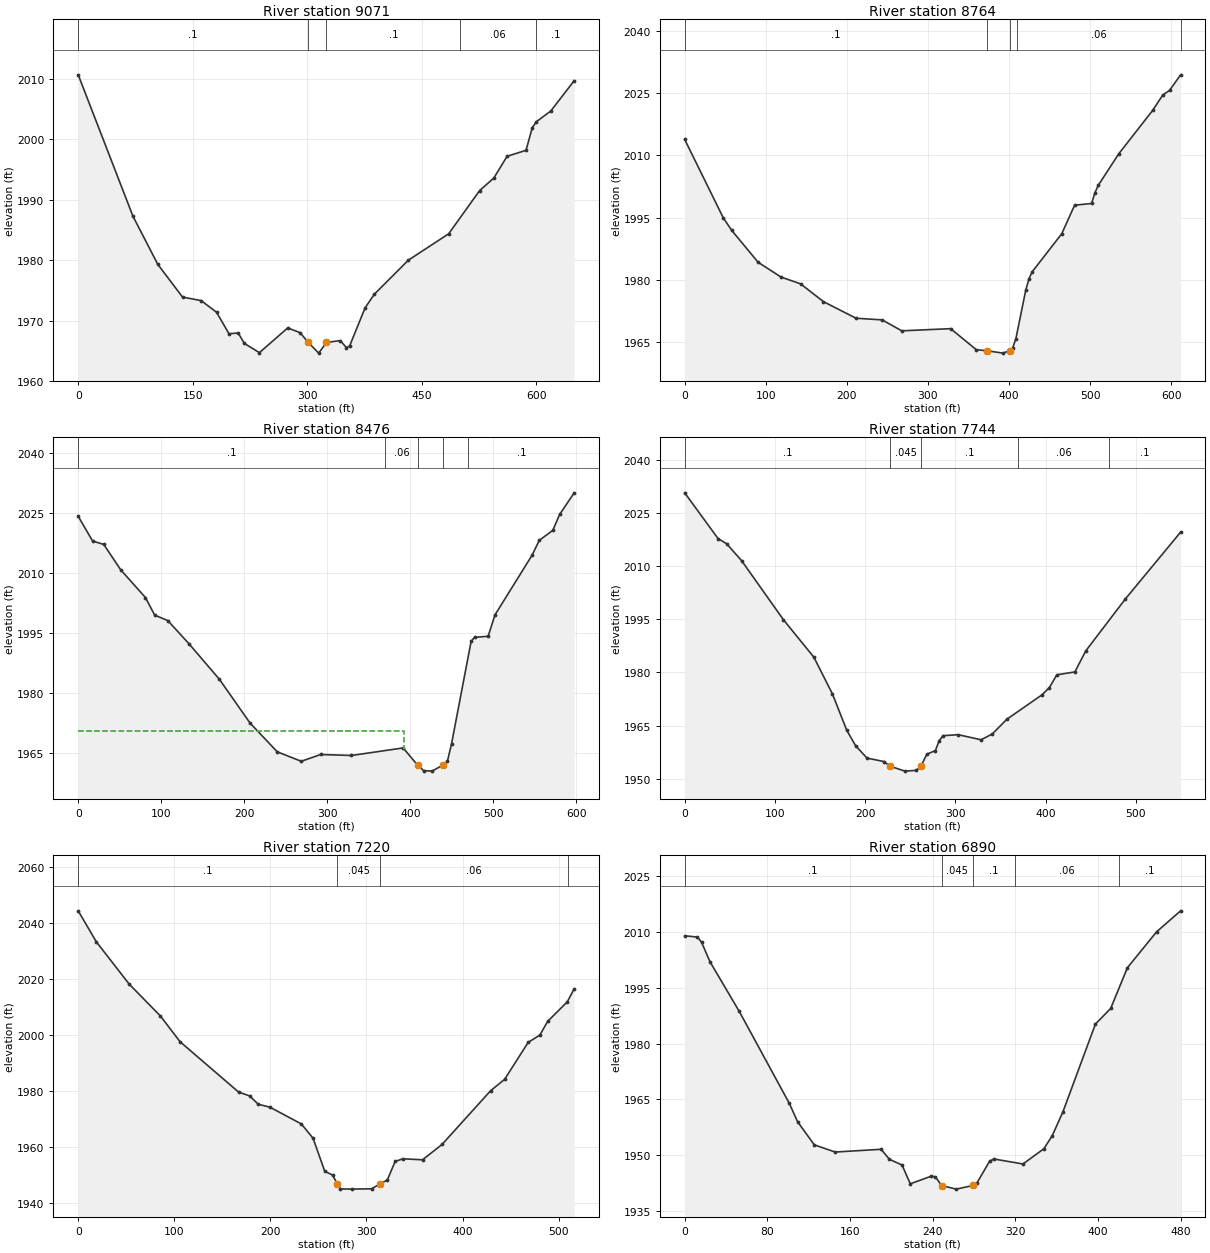
Type RM Length L Ch R = 1 ,9071    ,303.6,306.9,304.2
XS GIS Cut Line= 2
2228697.35877354674591.7749748282229338.42723069 674695.62407069
#Sta/Elev= 30
       0 2010.68    71.7 1987.26   104.2  1979.3   136.6 1973.88   160.9  1973.3
   181.1 1971.38   197.4 1967.81   209.5 1967.93   217.6  1966.2   237.3 1964.68
   274.3 1968.77   290.6 1967.99   300.51966.467   314.9  1964.6   325.11966.372
   343.2 1966.67   351.3 1965.51   355.4 1965.79   375.7 1972.11   387.8 1974.36
   432.4    1980   485.1 1984.36   525.6 1991.51   544.2 1993.59   561.6 1997.19
   586.4 1998.18   594.5 2001.91     600 2002.92   618.8 2004.69   649.4  2009.7
#Mann= 5, -1 ,  0
       0     0.1       0   300.5   0.045       0   325.1     0.1       0
     500    0.06       0     600     0.1       0
Bank Sta=300.5,325.1
XS Rating Curve= 0 ,0
Exp/Cntr(USF)=0,0
Exp/Cntr=0.3,0.1

Type RM Length L Ch R = 1 ,8764    ,285.7,287.4,289.2
XS GIS Cut Line= 3
2228682.06237683674886.9189167392229161.36589619 674938.84346467
2229285.18597202674976.788326619
#Sta/Elev= 30
       0 2013.81    47.5 1994.97    58.1 1991.89    90.6 1984.24   118.8 1980.68
   142.9 1979.05   171.1 1974.77   211.3 1970.77   243.6 1970.37   267.7 1967.74
     328 1968.26   359.7 1963.19   372.3 1962.96   392.4 1962.37  400.93 1962.96
   404.5  1963.6   408.5 1965.89   420.6  1977.5   424.6 1980.28   428.6 1981.96
     465  1991.1   480.9 1997.98   501.8 1998.39     506    2001   510.1 2002.78
   535.2 2010.32   577.1 2020.79   589.6 2024.49     598 2025.63   611.6 2029.36
#Mann= 5, -1 ,  0
       0     0.1       0   372.3   0.045       0  400.93     0.1       0
     410    0.06       0  611.61     0.1       0
Bank Sta=372.3,400.93
XS Rating Curve= 0 ,0
Exp/Cntr(USF)=0,0
Exp/Cntr=0.3,0.1

Type RM Length L Ch R = 1 ,8476    ,739.1,732.3,720.9
BEGIN DESCRIPTION:
Disconnected without IFA
END DESCRIPTION:
XS GIS Cut Line= 2
 2228626.1436329675122.5764804252229209.29624812675252.387850252
#Sta/Elev= 30
       0 2024.29    17.3 2018.11    30.8 2017.25    51.3 2010.88      81 2003.97
    92.2 1999.55   107.8 1998.23   133.2 1992.47   170.1 1983.52     207 1972.58
   239.8 1965.38   268.7 1963.02   292.1 1964.72     329 1964.47   391.4 1966.36
   408.81962.061     416  1960.7   426.2 1960.56   439.6  1962.1   444.7    1963
   449.7 1967.38   473.3 1993.01   477.4 1994.02   493.8 1994.29     502 1999.62
   546.9 2014.62   555.3 2018.26   571.7 2020.78   579.9 2024.74   597.4 2030.16
#Mann= 5, -1 ,  0
       0     0.1       0     370    0.06       0   408.8   0.045       0
   439.6    0.06       0     470     0.1       0
#XS Ineff= 2 , 0
          392.72 1970.62
Permanent Ineff=
       F       F
Bank Sta=408.8,439.6
XS Rating Curve= 0 ,0
Exp/Cntr(USF)=0,0
Exp/Cntr=0.3,0.1

Type RM Length L Ch R = 1 ,7744    ,517.2,524.4,524.7
XS GIS Cut Line= 3
2228636.12912289675643.8190577312229025.56323237675516.004785901
2229165.36009218675518.001883898
#Sta/Elev= 30
       0  2030.7      37 2017.79    46.5 2016.33    63.2 2011.52   109.5 1994.87
   143.2 1984.31   163.8 1973.93   179.6 1963.72   189.5 1959.31   202.1 1955.84
   220.8 1954.87   227.8 1953.53   244.2 1952.16   256.9 1952.38  261.761953.481
   268.4 1956.93   277.9 1957.97   282.1 1960.74   286.3 1962.16   303.2 1962.44
   328.6 1961.01   341.1 1962.68   357.1  1966.8   395.8 1973.65   404.2 1975.72
   412.5 1979.34   432.5 1980.16   444.5 1986.07   488.4 2000.73   549.7 2019.61
#Mann= 5, -1 ,  0
       0     0.1       0   227.8   0.045       0  261.76     0.1       0
     370    0.06       0  469.87     0.1       0
Bank Sta=227.8,261.76
XS Rating Curve= 0 ,0
Exp/Cntr(USF)=0,0
Exp/Cntr=0.3,0.1

Type RM Length L Ch R = 1 ,7220    ,329.1,330,330.5
XS GIS Cut Line= 2
2228688.05367082676095.1632051292229195.31656214675999.302501257
#Sta/Elev= 30
       0 2044.32    18.9 2033.25      53 2018.22    85.6 2006.81     106 1997.66
     167 1979.68   178.4 1978.35   187.4 1975.36   199.6 1974.31   232.2 1968.35
   244.4 1963.27   256.6 1951.47   264.7 1950.11  269.781946.951   272.9 1945.18
   285.1  1945.1   305.4 1945.22   313.6 1946.86   321.7 1948.34   329.9 1954.98
     338 1955.91   358.4 1955.56   378.7 1961.03   429.3 1980.21   443.8 1984.23
   468.3  1997.4   480.5 2000.03   488.6 2004.89     509 2011.85   516.2 2016.49
#Mann= 4, -1 ,  0
       0     0.1       0  269.78   0.045       0   313.6    0.06       0
     510     0.1       0
Bank Sta=269.78,313.6
XS Rating Curve= 0 ,0
Exp/Cntr(USF)=0,0
Exp/Cntr=0.3,0.1

Type RM Length L Ch R = 1 ,6890    ,232.5,232.8,232.3
XS GIS Cut Line= 2
2228771.93178671 676402.716296722229247.24111007 676334.81496481
#Sta/Elev= 30
       0 2008.98    12.4 2008.64    16.4 2007.21    24.5    2002    52.8 1988.67
   101.3 1963.94   109.3    1959   125.5 1952.78   145.7 1950.85   190.2 1951.59
   198.2 1948.89   210.4 1947.37   218.4 1942.31   238.6 1944.35   242.7  1944.2
  248.691941.848   262.9 1940.88     279 1941.86   283.1 1942.61   295.2 1948.39
   299.3 1948.98   327.5 1947.64   347.7 1951.73   355.8 1955.22   366.2 1961.68
   397.6 1985.24   412.4 1989.45   428.6 2000.41   456.8 2010.04   480.1 2015.69
#Mann= 5, -1 ,  0
       0     0.1       0  248.69   0.045       0     279     0.1       0
     320    0.06       0     420     0.1       0
Bank Sta=248.69,279
XS Rating Curve= 0 ,0
Exp/Cntr(USF)=0,0
Exp/Cntr=0.3,0.1

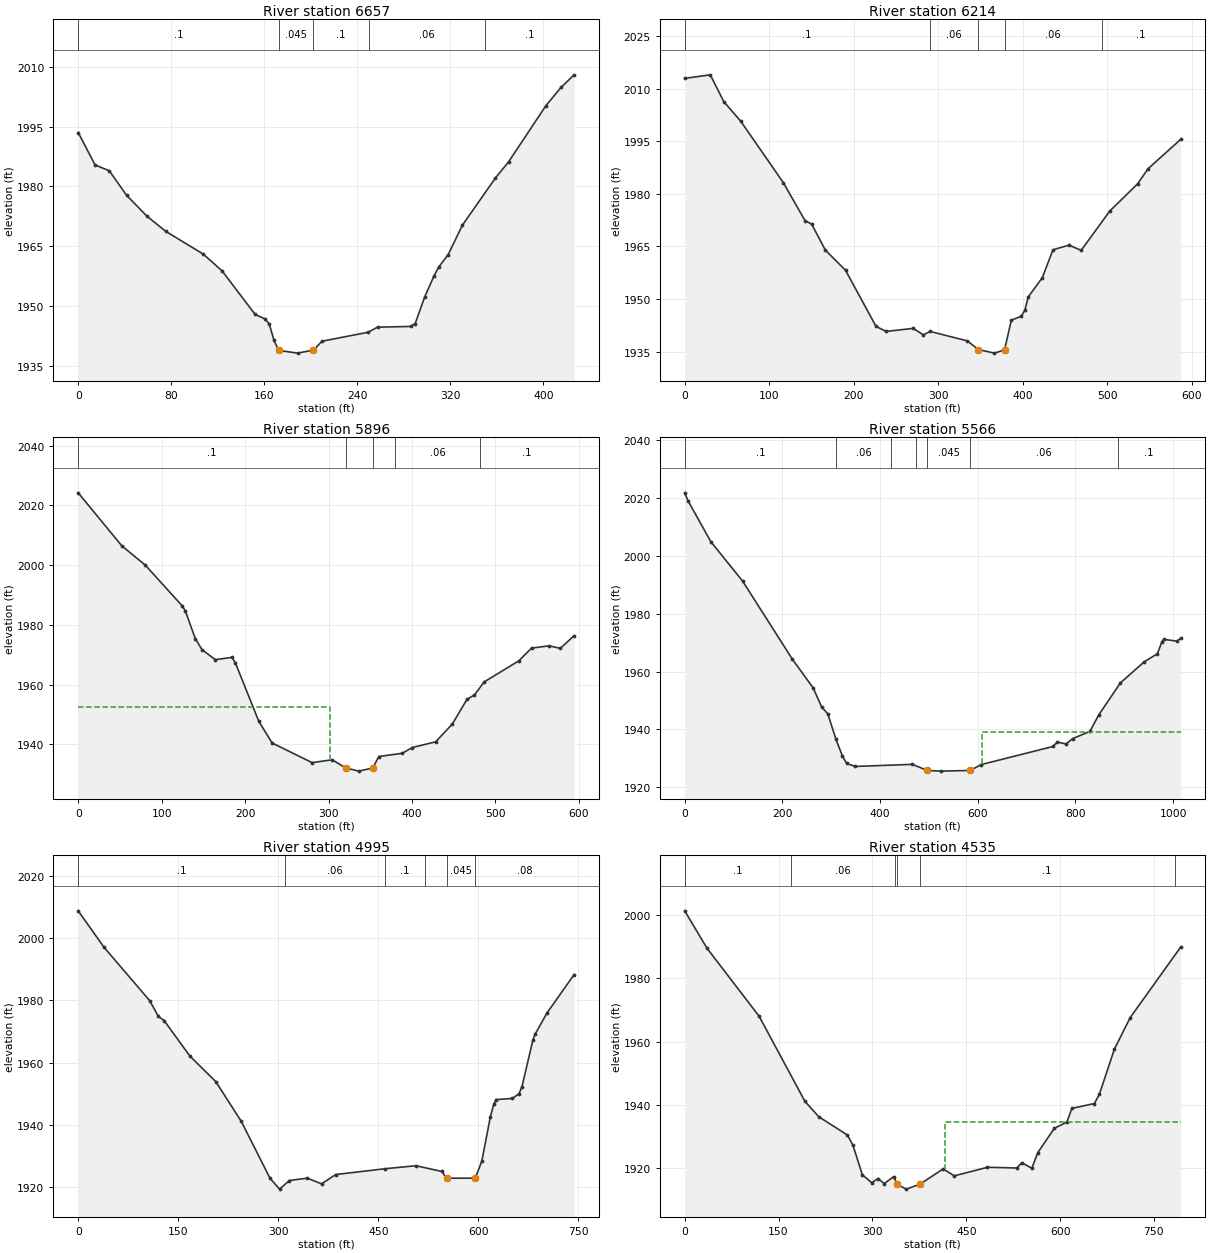
Type RM Length L Ch R = 1 ,6657    ,441,442.8,444.8
XS GIS Cut Line= 2
2228845.82441261676626.3912724222229267.21209005676560.487038509
#Sta/Elev= 30
       0 1993.52    14.5  1985.4    26.7 1983.94    41.6  1977.8    59.1 1972.56
    75.3 1968.76   107.6 1963.05   123.8 1958.83   152.2 1947.93   160.3 1946.86
   164.2 1945.62   168.4 1941.44   172.4 1938.94   188.6 1938.25  202.241938.999
   209.7 1941.24   249.3 1943.47   257.4 1944.76   285.8 1944.93   289.8 1945.66
   297.9 1952.28     306  1957.6   310.1 1959.85   318.2 1962.93   330.3 1970.27
   358.7 1982.09   370.3 1986.25   402.2 2000.24   415.3 2004.86   426.5 2007.98
#Mann= 5, -1 ,  0
       0     0.1       0   172.4   0.045       0  202.24     0.1       0
     250    0.06       0     350     0.1       0
Bank Sta=172.4,202.24
XS Rating Curve= 0 ,0
Exp/Cntr(USF)=0,0
Exp/Cntr=0.3,0.1

Type RM Length L Ch R = 1 ,6214    ,316.3,317.9,317
XS GIS Cut Line= 3
2228797.89406067677033.7992638792229201.30785613  677017.8224799
 2229377.0524799676965.897931969
#Sta/Elev= 30
       0  2012.9    30.3 2013.92    46.3 2006.28    66.3 2000.72   116.8 1983.16
   142.4 1972.38   150.4 1971.33   166.4 1963.98   190.4 1958.19   226.5 1942.19
   238.5 1940.76   270.5 1941.64   282.5 1939.78   290.5 1940.76   334.5 1938.07
   347.7  1935.6   366.6 1934.58   378.6  1935.5   386.6 1943.95   398.6 1945.12
   402.6 1946.83   406.7 1950.62   423.4 1956.11   435.9 1964.05   454.9 1965.36
   469.3 1963.88   503.1 1975.07     536 1982.82   548.5 1987.16     587  1995.5
#Mann= 5, -1 ,  0
       0     0.1       0     290    0.06       0   347.7   0.045       0
   378.6    0.06       0  493.73     0.1       0
Bank Sta=347.7,378.6
XS Rating Curve= 0 ,0
Exp/Cntr(USF)=0,0
Exp/Cntr=0.3,0.1

Type RM Length L Ch R = 1 ,5896    ,384.1,329.7,302.3
XS GIS Cut Line= 3
2228803.88535466677329.3697674852229255.22950206677323.378473493
2229383.04377389677259.471337578
#Sta/Elev= 30
       0 2024.18    52.3 2006.43    80.3 2000.02   124.3 1986.46   128.3 1984.72
   140.3 1975.41   148.3 1971.73   164.3 1968.36   184.3 1969.13   188.3  1967.3
   216.3  1947.8   232.3  1940.5   280.3  1933.9   304.3 1934.87  320.58 1932.14
     336 1931.07   352.8 1932.09   360.3 1935.96   388.3 1937.04   400.3 1938.96
   428.3 1940.87   448.3 1946.82   465.9  1955.1   474.8 1956.54   486.5 1960.93
   527.9 1967.95   543.2 1972.22   564.2    1973   577.7 1972.16   594.3 1976.38
#Mann= 5, -1 ,  0
       0     0.1       0  320.58   0.045       0   352.8     0.1       0
     380    0.06       0  481.38     0.1       0
#XS Ineff= 2 , 0
          301.86 1952.63
Permanent Ineff=
       F       F
Bank Sta=320.58,352.8
XS Rating Curve= 0 ,0
Exp/Cntr(USF)=0,0
Exp/Cntr=0.3,0.1

Type RM Length L Ch R = 1 ,5566    ,502.7,571,601.8
XS GIS Cut Line= 6
2228697.99885925 677695.368749582229031.77437263677821.394622441
2229100.54918887677690.7224715832229133.21722659677603.894266079
2229161.58683829 677458.607466772229402.92144745677340.594296672
#Sta/Elev= 30
       0 2021.74     6.6 2019.06    53.6 2004.85   118.4 1991.31   220.4 1964.28
   263.1 1954.35   280.2 1947.85   293.1 1945.36   309.7 1936.61     323 1930.83
   331.5 1928.28   348.7 1927.24     466 1927.96  496.611925.854   524.6 1925.62
   584.5 1925.85   606.9 1927.87     754 1934.13   762.9 1935.68   780.7    1935
   794.1 1936.82   829.7 1939.35   847.5 1944.98   892.1 1956.11     941  1963.4
   967.8 1966.17     977 1970.28   981.1 1971.13  1007.8 1970.51  1015.3 1971.49
#Mann= 7, -1 ,  0
       0     0.1       0     310    0.06       0  422.48     0.1       0
  474.26    0.06       0  496.61   0.045       0   584.5    0.06       0
  886.69     0.1       0
#XS Ineff= 2 , 0
                          608.23         1939.29
Permanent Ineff=
       F       F
Bank Sta=496.61,584.5
XS Rating Curve= 0 ,0
Exp/Cntr(USF)=0,0
Exp/Cntr=0.3,0.1

Type RM Length L Ch R = 1 ,4995    ,442.3,460.5,466.7
XS GIS Cut Line= 2
2228600.18135893677998.3975965942229293.17436401678268.005826235
#Sta/Elev= 30
       0  2008.7    38.6 1997.02   107.2 1979.88   120.2 1974.82   128.8 1973.51
   167.4 1962.11   206.3  1953.9   244.6 1941.11   287.6 1922.89   301.9 1919.41
   316.6 1922.17   343.4 1922.93   364.8 1921.11   386.3  1924.1     460 1925.95
   506.5 1926.92   545.1 1925.08   552.2 1922.92   595.4 1922.92   605.2 1928.42
     618 1942.65   623.2 1946.69   626.6 1948.14     651 1948.49     661 1950.05
   665.3 1952.26   681.9 1967.37     685 1969.09   702.7 1975.87   743.6 1988.27
#Mann= 6, -1 ,  0
       0     0.1       0     310    0.06       0     460     0.1       0
     520    0.08       0   552.2   0.045       0   595.4    0.08       0
Bank Sta=552.2,595.4
XS Rating Curve= 0 ,0
Exp/Cntr(USF)=0,0
Exp/Cntr=0.3,0.1

Type RM Length L Ch R = 1 ,4535    ,403,384.5,359.8
XS GIS Cut Line= 4
2228488.34387108678283.982610214 2228726.4181061678402.848439823
2228814.50580375678520.5116178742229194.03920141678518.006403104
#Sta/Elev= 30
       0  2001.4    35.6 1989.59   119.1 1968.01   192.1 1941.16   214.4 1936.24
   260.2 1930.46     269 1927.19     284 1917.87     299 1915.38     309 1916.72
     319 1915.11     334 1917.32  339.63 1914.91     354 1913.36   375.8 1914.89
   413.1 1919.76   430.8 1917.56   483.9 1920.27   530.8 1920.05   538.8 1921.69
   554.8 1919.97   564.4 1924.94   590.8  1932.6   610.8 1934.56   618.8 1938.91
   654.8 1940.44   662.8 1943.39   686.8 1957.67   712.1 1967.65   792.6  1989.9
#Mann= 6, -1 ,  0
       0     0.1       0     170    0.06       0   336.1     0.1       0
  339.63   0.045       0   375.8     0.1       0  783.08    0.08       0
#XS Ineff= 2 , 0
                          415.37         1934.46
Permanent Ineff=
       F       F
Bank Sta=339.63,375.8
XS Rating Curve= 0 ,0
Exp/Cntr(USF)=0,0
Exp/Cntr=0.3,0.1

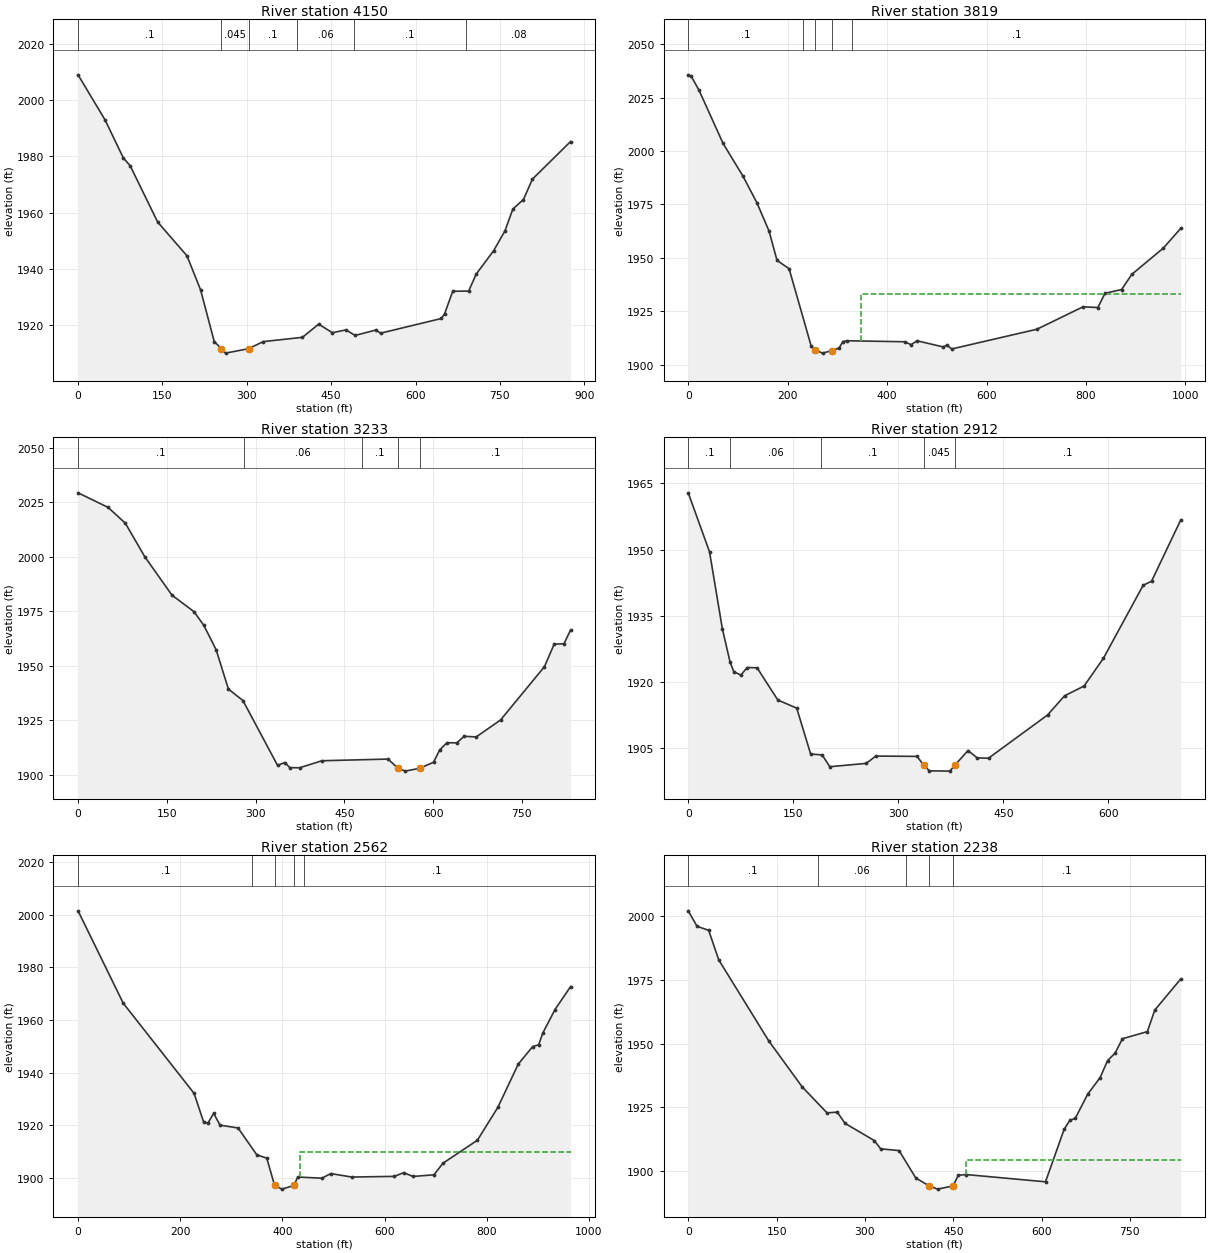
Type RM Length L Ch R = 1 ,4150    ,331.3,331.9,332.1
XS GIS Cut Line= 3
2228408.45995119678833.1845594822229107.44425026678735.326757613
2229235.25852209678623.489269761
#Sta/Elev= 30
       0  2008.9    48.2 1992.85    80.5 1979.42    92.6 1976.68   141.5 1956.69
   193.6 1944.71   217.8 1932.65   242.1 1914.29   254.8 1911.78   262.2 1910.18
  303.151911.759   329.3 1914.27   398.9 1915.78   427.8 1920.47   452.1 1917.42
   476.3 1918.42   492.5 1916.46   528.8 1918.34   538.3 1917.28     646 1922.47
   651.7 1924.18   666.1 1932.13   694.4 1932.19   707.8  1938.2   738.7 1946.49
   758.9 1953.54     773  1961.3   791.8 1964.67   807.8 1971.92   875.6 1985.24
#Mann= 6, -1 ,  0
       0     0.1       0   254.8   0.045       0  303.15     0.1       0
     390    0.06       0     490     0.1       0     690    0.08       0
Bank Sta=254.8,303.15
XS Rating Curve= 0 ,0
Exp/Cntr(USF)=0,0
Exp/Cntr=0.3,0.1

Type RM Length L Ch R = 1 ,3819    ,573.1,585.2,591.8
XS GIS Cut Line= 3
2228466.59031026679150.8116800162229274.80634177679064.627582019
2229423.88778022679161.839421806
#Sta/Elev= 30
       0 2035.68     5.6 2035.14    21.7 2028.46      70 2003.61   110.2 1988.21
   138.4 1975.67   162.5 1962.58   178.6 1948.84   202.9 1944.92     247 1908.99
   254.41907.065   270.1 1905.43   289.11906.627   303.3  1907.8   311.3 1910.85
   319.2 1911.22     436 1910.75   448.1 1909.37   460.2  1911.2   512.5 1908.36
   520.5 1909.16     530 1907.38   701.5 1916.62   794.1 1927.11     824 1926.77
   838.3 1933.44   871.7  1935.2   892.2 1942.28   955.8 1954.61   990.8 1963.85
#Mann= 5, -1 ,  0
       0     0.1       0     230    0.06       0   254.4   0.045       0
   289.1    0.06       0     330     0.1       0
#XS Ineff= 2 , 0
                          346.62         1933.26
Permanent Ineff=
       F       F
Bank Sta=254.4,289.1
XS Rating Curve= 0 ,0
Exp/Cntr=0.3,0.1

Type RM Length L Ch R = 1 ,3233    ,309,320.9,329.1
XS GIS Cut Line= 3
2228427.15586195 679375.586668092229049.26299786679546.748799734
2229231.18211802679590.532125236
#Sta/Elev= 30
       0 2029.39    50.8 2022.71    79.9 2015.46   112.7 2000.12   158.7 1982.48
     196 1974.88   212.6  1968.6   233.4 1957.39   254.1  1939.4   278.7 1934.11
   337.1 1904.43   349.5 1905.71   357.8 1903.36   374.4 1903.32   412.1 1906.53
   523.8  1907.3   540.4 1903.15   552.8 1901.77   577.7  1903.1   600.8 1905.86
   610.9 1911.43   623.5 1914.81   639.9 1914.73   652.3 1917.74   672.9 1917.47
     714 1925.24   788.1 1949.66   804.6 1960.02     821 1960.16   832.3 1966.46
#Mann= 5, -1 ,  0
       0     0.1       0     280    0.06       0     480     0.1       0
   540.4   0.045       0   577.7     0.1       0
Bank Sta=540.4,577.7
XS Rating Curve= 0 ,0
Exp/Cntr=0.3,0.1

Type RM Length L Ch R = 1 ,2912    ,380.8,350.8,337.2
XS GIS Cut Line= 3
 2228552.6346737679537.7503286792228847.74255479679814.216363439
2229145.79354972679838.548348801
#Sta/Elev= 30
       0 1962.86    30.4 1949.49    48.7 1932.09    59.7 1924.56    65.1 1922.35
    75.2  1921.6    84.2  1923.3    98.3 1923.24   127.9 1915.95   154.9  1914.1
   174.8 1903.72   191.2 1903.51   202.2 1900.84     254 1901.59   267.9 1903.25
   326.8 1903.18     336 1901.24   344.4 1899.91   373.6 1899.84  381.14 1901.26
   399.5  1904.5   412.8 1902.83   428.9 1902.78   513.2 1912.56   537.4  1916.9
   565.3 1919.11     593 1925.42   649.6 1941.91   661.7 1942.86   703.4 1956.74
#Mann= 5, -1 ,  0
       0     0.1       0      60    0.06       0     190     0.1       0
     336   0.045       0  381.14     0.1       0
Bank Sta=336,381.14
XS Rating Curve= 0 ,0
Exp/Cntr(USF)=0,0
Exp/Cntr=0.3,0.1

Type RM Length L Ch R = 1 ,2562    ,333.2,323.6,321.4
XS GIS Cut Line= 5
2228332.06495023680295.7858962582228542.73565962680109.150083142
 2228748.0053993680025.4169456192228943.33311332679912.451993795
2229178.68496333679910.718359659
#Sta/Elev= 30
       0 2001.45    88.4 1966.41   227.1 1932.18   245.6 1921.43   254.1 1920.82
   265.4  1924.6     278  1920.1   313.2 1919.03     350 1908.82   369.4 1907.59
  384.77 1897.22   399.1 1895.82   422.8 1897.23   429.9 1900.41   477.4 1899.97
   494.7 1901.73   535.6 1900.41   618.9 1900.66   637.3 1902.05   655.7 1900.63
   696.7 1901.26   714.2 1905.64   781.6 1914.36   821.6 1926.81   861.6 1943.24
   889.6 1949.87   901.6 1950.62   909.6 1955.01   933.6 1963.99   964.1  1972.7
#Mann= 5, -1 ,  0
       0     0.1       0  341.45    0.06       0  384.77   0.045       0
   422.8    0.06       0  441.45     0.1       0
#XS Ineff= 2 , 0
                          434.12         1910.03
Permanent Ineff=
       F       F
Bank Sta=384.77,422.8
XS Rating Curve= 0 ,0
Exp/Cntr(USF)=0,0
Exp/Cntr=0.3,0.1

Type RM Length L Ch R = 1 ,2238    ,420.3,433.3,443.9
XS GIS Cut Line= 3
2228565.23214398680567.2248086132229055.60455942680143.484833582
2229234.02032133680083.567615617
#Sta/Elev= 30
       0 2002.15    14.9  1996.1    34.7 1994.48    51.7 1982.93   136.8 1951.05
   193.5 1933.02   235.6 1922.83   253.1 1923.11   266.2  1918.7   315.8 1911.97
   326.8  1908.7     358 1908.01   386.4 1897.24   409.1 1894.15   423.3 1892.88
   449.7 1894.14   458.5 1898.29   471.5 1898.61   606.6 1895.76   638.3 1916.41
   648.1 1919.95   657.1 1920.63   678.2 1930.16   699.3 1936.66     712 1943.35
   724.6 1946.25   737.3 1951.94   779.5 1954.72   792.2 1963.22   836.3 1975.42
#Mann= 5, -1 ,  0
       0     0.1       0     220    0.06       0     370     0.1       0
   409.1   0.045       0   449.7     0.1       0
#XS Ineff= 2 , 0
                          472.07         1904.39
Permanent Ineff=
       F       F
Bank Sta=409.1,449.7
XS Rating Curve= 0 ,0
Exp/Cntr(USF)=0,0
Exp/Cntr=0.3,0.1

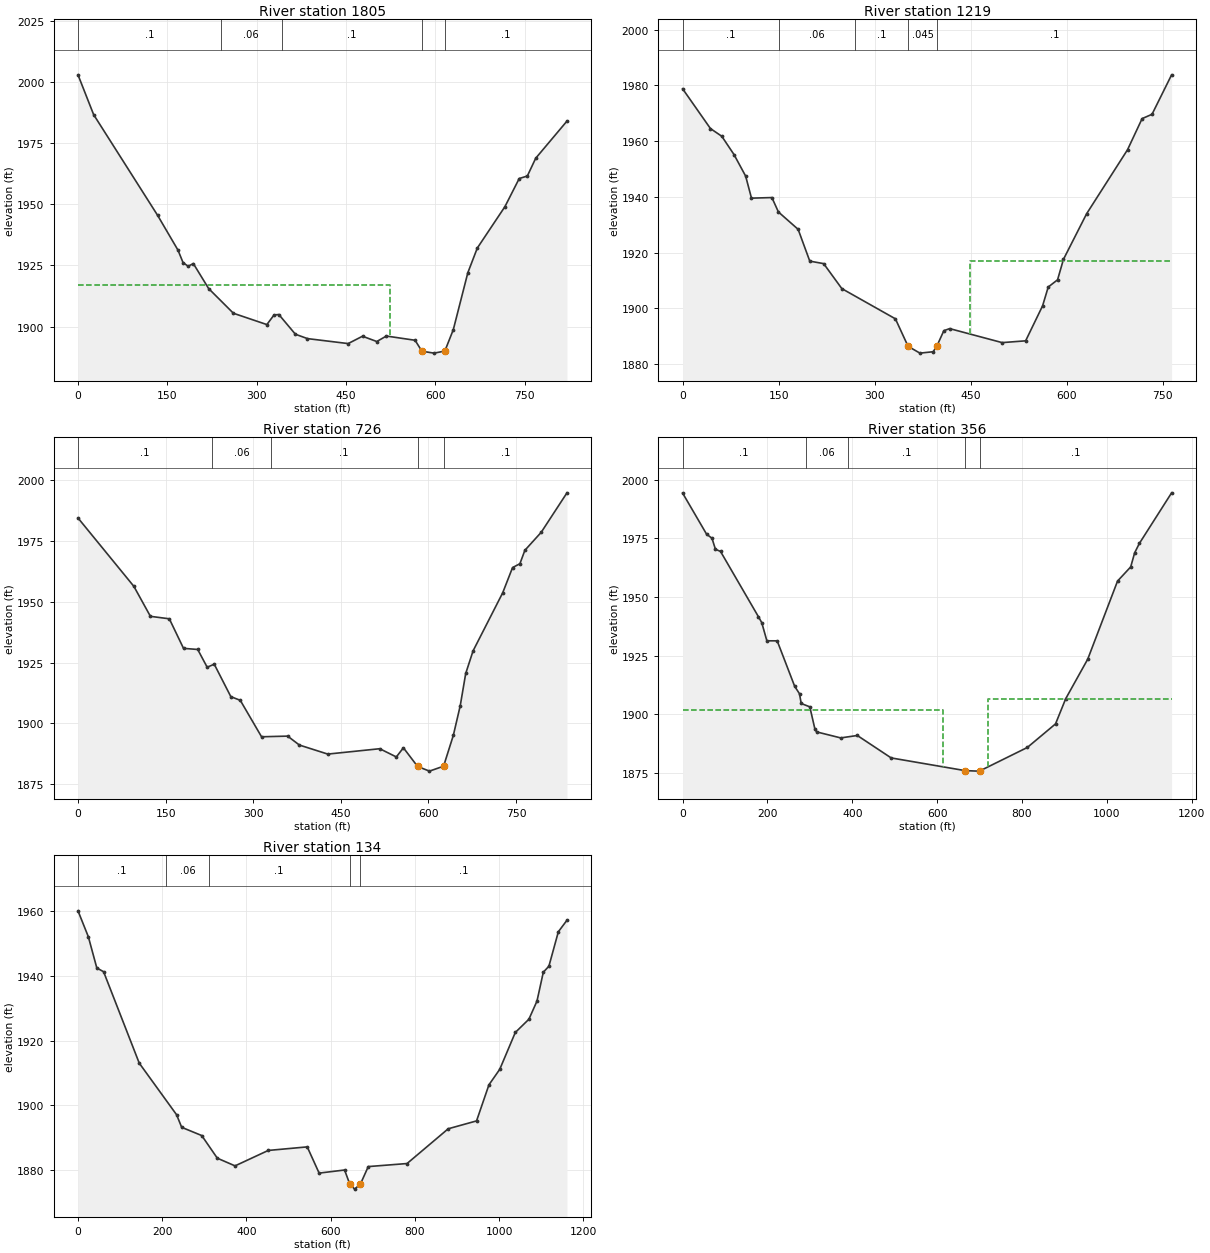
Type RM Length L Ch R = 1 ,1805    ,592.7,585.4,574.4
XS GIS Cut Line= 4
2228663.64913329680646.8091638062228889.21107905680559.228056751
2229314.65286542680523.6397704382229452.48287126680458.862271277
#Sta/Elev= 30
       0 2002.84    26.3 1986.57   133.6  1945.5   167.9 1931.26   176.5 1926.12
   185.1 1924.67   193.7 1925.77   219.4 1915.56     261 1905.47   317.2 1900.85
   329.2 1904.77   337.3 1904.96   365.1 1896.91   385.4 1895.12   453.7 1893.09
   477.8 1896.09   501.8 1893.93   517.9 1896.17   566.1 1894.44  577.571889.974
   597.8 1889.19616.06021890.012   630.3 1898.78   654.7 1922.03   670.6  1932.1
     717 1949.01     741  1960.5   754.6 1961.51   768.7 1968.78   821.2 1983.95
#Mann= 5, -1 ,  0
       0     0.1       0     240    0.06       0  341.97     0.1       0
  577.57   0.045       0616.0602     0.1       0
#XS Ineff= 2 , 0
          524.08 1917.17
Permanent Ineff=
       F       F
Bank Sta=577.57,616.0602
XS Rating Curve= 0 ,0
Exp/Cntr(USF)=0,0
Exp/Cntr=0.3,0.1

Type RM Length L Ch R = 1 ,1219    ,483.4,493.8,512.1
XS GIS Cut Line= 2
2228953.66770446681233.6963522852229624.69263157680868.227418772
#Sta/Elev= 30
       0 1978.77    43.5 1964.51    61.2 1961.75    80.3 1955.19    98.5 1947.46
   107.6 1939.56   139.5 1939.77   149.7  1934.6   180.5 1928.38   198.7 1916.98
   220.4 1916.08   248.8 1907.12   332.5 1896.29   352.3 1886.43   370.8 1883.99
   391.5 1884.49   397.4 1886.57   408.2 1892.04   417.3 1892.78   499.3 1887.76
     536  1888.4   562.5 1900.95   571.3 1907.69   585.9 1910.28   595.1 1917.62
   631.4 1934.01   695.2 1956.91     718 1968.08   733.5 1969.63   764.1 1983.78
#Mann= 5, -1 ,  0
       0     0.1       0     150    0.06       0     270     0.1       0
   352.3   0.045       0   397.4     0.1       0
#XS Ineff= 2 , 0
                          449.39         1917.03
Permanent Ineff=
       F       F
Bank Sta=352.3,397.4
XS Rating Curve= 0 ,0
Exp/Cntr(USF)=0,0
Exp/Cntr=0.3,0.1

Type RM Length L Ch R = 1 ,726     ,361.6,369.1,374.4
XS GIS Cut Line= 3
2228957.66190046681349.5280361312229582.75357363   681447.385838
2229776.47207937681381.481604088
#Sta/Elev= 30
       0 1984.53    95.7 1956.36     124 1944.02   156.4    1943   180.7 1930.83
     205 1930.37   221.2 1923.05   233.3 1924.31   261.7 1910.94   277.9 1909.42
   314.3 1894.41     359 1894.68   379.1    1891   427.7 1887.28   516.7 1889.49
   545.1  1886.1   557.2 1889.87   581.5 1882.19   601.8 1880.26     626 1882.29
   642.7 1894.99   654.5 1907.17   663.9 1920.48   676.5 1929.79   727.2 1953.69
   744.1  1964.1   756.7 1965.69   765.2 1971.21   793.2 1978.64   837.3 1994.89
#Mann= 5, -1 ,  0
       0     0.1       0     230    0.06       0     330     0.1       0
   581.5   0.045       0     626     0.1       0
Bank Sta=581.5,626
XS Rating Curve= 0 ,0
Exp/Cntr(USF)=0,0
Exp/Cntr=0.3,0.1

Type RM Length L Ch R = 1 ,356     ,230.1,222.7,214.6
XS GIS Cut Line= 6
2228899.74605854681597.1681878012229351.09020594 681665.06951971
 2229452.9422038681728.9766556252229508.86094772681802.869281527
2229700.58235547681848.8025354662229924.25733117681675.055009697
#Sta/Elev= 30
       0 1994.37    56.6 1976.81    69.2 1975.12    77.3 1970.42    89.4 1969.47
   178.4 1941.73   186.5 1939.13   198.6 1931.36   222.9 1931.35   264.1 1911.97
   275.5 1908.77   279.5 1904.63   299.8  1903.2   311.9 1893.66   315.9 1892.51
   372.6 1889.95   411.8 1890.98   491.6 1881.41   665.7    1876   696.4 1875.78
   702.11876.008   812.5 1885.87     879 1895.93     903 1906.68   954.9 1923.54
  1025.2 1956.85  1056.2 1962.89  1065.5  1968.9  1076.5 1972.87  1152.6 1994.48
#Mann= 5, -1 ,  0
       0     0.1       0     290    0.06       0     390     0.1       0
   665.7   0.045       0   702.1     0.1       0
#XS Ineff= 2 , 0
           614.3 1901.76     720         1906.34
Permanent Ineff=
       F       F
Bank Sta=665.7,702.1
XS Rating Curve= 0 ,0
Exp/Cntr(USF)=0,0
Exp/Cntr=0.3,0.1

Type RM Length L Ch R = 1 ,134     ,,,
XS GIS Cut Line= 3
2228875.78088257 681950.654533332229668.62878751682046.515237202
2229952.21670313681820.843163503
#Sta/Elev= 30
       0 1960.06    24.6 1952.05    44.7 1942.42    60.8 1941.26   145.4 1913.05
   234.1 1897.11   246.2 1893.23   293.8 1890.69   330.8  1883.7   372.9 1881.33
   451.7 1886.09   544.3 1887.19   572.5  1879.1     633 1880.05   645.1 1875.76
   656.8 1874.15  670.621875.734   689.2 1881.11   781.3 1882.05     879 1892.78
   946.3 1895.21   975.7 1906.35  1001.4 1911.14  1038.3 1922.51  1070.6  1926.6
  1089.8 1932.21  1104.8 1941.11  1118.1 1942.97  1140.5  1953.6    1161 1957.16
#Mann= 5, -1 ,  0
       0     0.1       0     210    0.06       0     310     0.1       0
   645.1   0.045       0  670.62     0.1       0
Bank Sta=645.1,670.62
XS Rating Curve= 0 ,0
Exp/Cntr(USF)=0,0
Exp/Cntr=0.3,0.1
LCMann Table=0

Chan Stop Cuts=-1
Use User Specified Reach Order=0
Composite Channel Slope=5